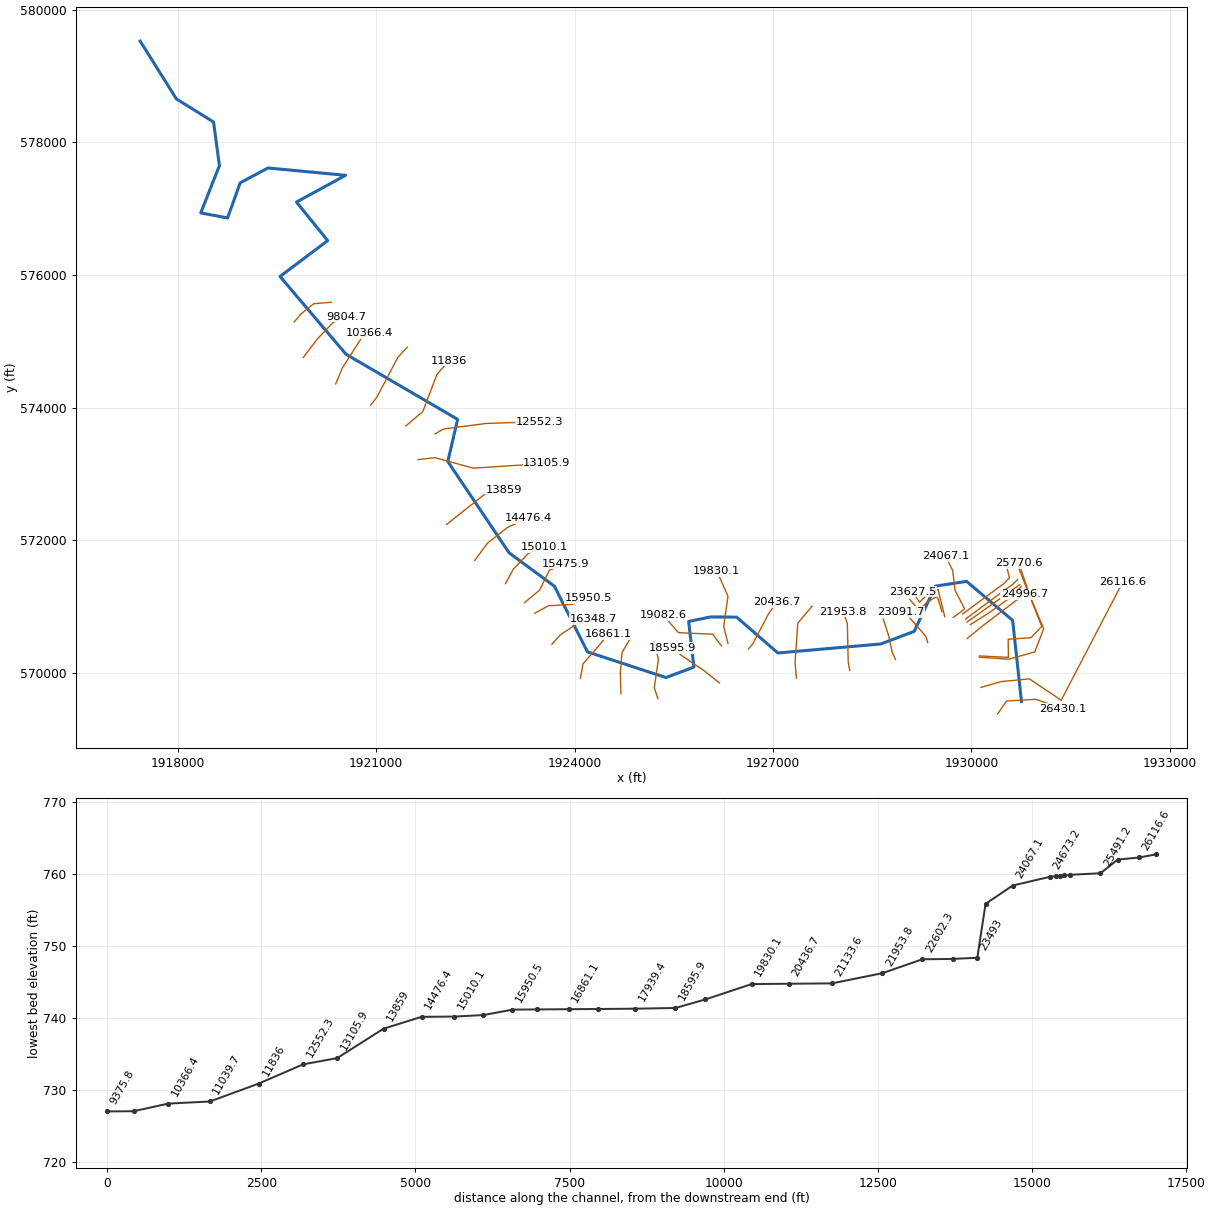
--- RFBgSndyCk.prj (project) ---

Proj Title=RFBgSndyCk
Current Plan=p01
Default Exp/Contr=0,0
English Units
Geom File=g01
Flow File=f01
Plan File=p01
BEGIN DESCRIPTION:
AMEC Environment & Infrastructure, 2013
Projection: NAD 1983 State Plane West Virginia South FIPS 4702 (US Feet)
Vertical Datum: NAVD 1988
END DESCRIPTION:
DSS Export Rating Curves= 0
DSS Export Rating Curve Sorted= 0
DSS Export Volume Flow Curves= 0
DXF OffsetX= 0
DXF OffsetY= 0
DXF ScaleX= 0
DXF ScaleY= 0

--- RFBgSndyCk.p01 (plan) ---

Plan Title=Floodplain
Program Version=4.00
Geom File=g01
Flow File=f01
K Sum by GR=0
Std Step Tol=0.01
Critical Tol=0.01
Num of Std Step Trials=20
Max Error Tol=0.3
Flow Tol Ratio=0.001
Split Flow NTrial=30
Split Flow Tol=0.02
Split Flow Ratio=0.02
Log Output Level=0
Friction Slope Method=1
Unsteady Friction Slope Method=2
Unsteady Bridges Friction Slope Method=1
Global Log Level=0
CheckData=False
Run HTab=0
Run UNet=0
Run PostProcess=0
UNET Theta=0
UNET Theta Warmup=0
UNET ZTol=0
UNET ZSATol=0
UNET MxIter=0
UNET MaxInSteps=0
UNET DtIC=0
UNET DtMin=0
UNET MaxCRTS=0
UNET WFStab=0
UNET SFStab=0
UNET WFX=0
UNET SFX=0
UNET DSS MLevel=0
UNET DZMax Abort=0
UNET Convert EG Bridges=0
UNET Use Existing IB Tables=0
UNET Froude Limit=0
UNET Froude Power=0
Write IC File=0
Echo Input=False
Echo Output=False
Write Detailed=0

--- RFBgSndyCk.f01 (steady flow) ---

Flow Title=NFF Regression Equation
Program Version=4.10
Number of Profiles= 1
Profile Names=P100yr
River Rch & RM=RFBgSndyCk,Main            ,26430.1
3399.256
River Rch & RM=RFBgSndyCk,Main            ,13859
3672.964
River Rch & RM=RFBgSndyCk,Main            ,349
4059.007
River Rch & RM=RFBgSndyCk,Main            ,45.7
4059.309
Boundary for River Rch & Prof#=RFBgSndyCk,Main            , 1
Up Type= 0
Dn Type= 3
Dn Slope=0.002
DSS Import GetInterval= 0
DSS Import GetPeak= 0
DSS Import FillOption= 0

--- RFBgSndyCk.g01 (geometry) ---

Geom Title=USGS 3m DEM
Program Version=4.10

River Reach=RFBgSndyCk      ,Main
Reach XY= 30
     1930758.209      569567.466     1930624.502      570791.252
     1929928.073      571378.252     1929457.872      571306.501
     1929136.141      570624.509     1928631.337      570434.547
     1927075.364      570298.545     1926449.445      570839.826
     1926051.738      570841.558     1925725.237      570773.821
     1925805.135      570086.085     1925383.116      569928.038
       1924195.2      570315.308     1923695.541      571305.249
     1923009.873      571808.863     1922083.442      573185.675
     1922231.796      573821.701     1920543.218      574803.642
     1919546.326      575975.907     1920266.805      576516.532
     1919794.688      577097.668     1920537.417      577501.032
     1919363.944      577611.889     1918943.663      577387.846
     1918752.633      576858.145     1918347.512      576934.574
     1918629.314      577646.611      1918540.73      578304.824
     1917978.553      578653.267     1917431.317      579524.516

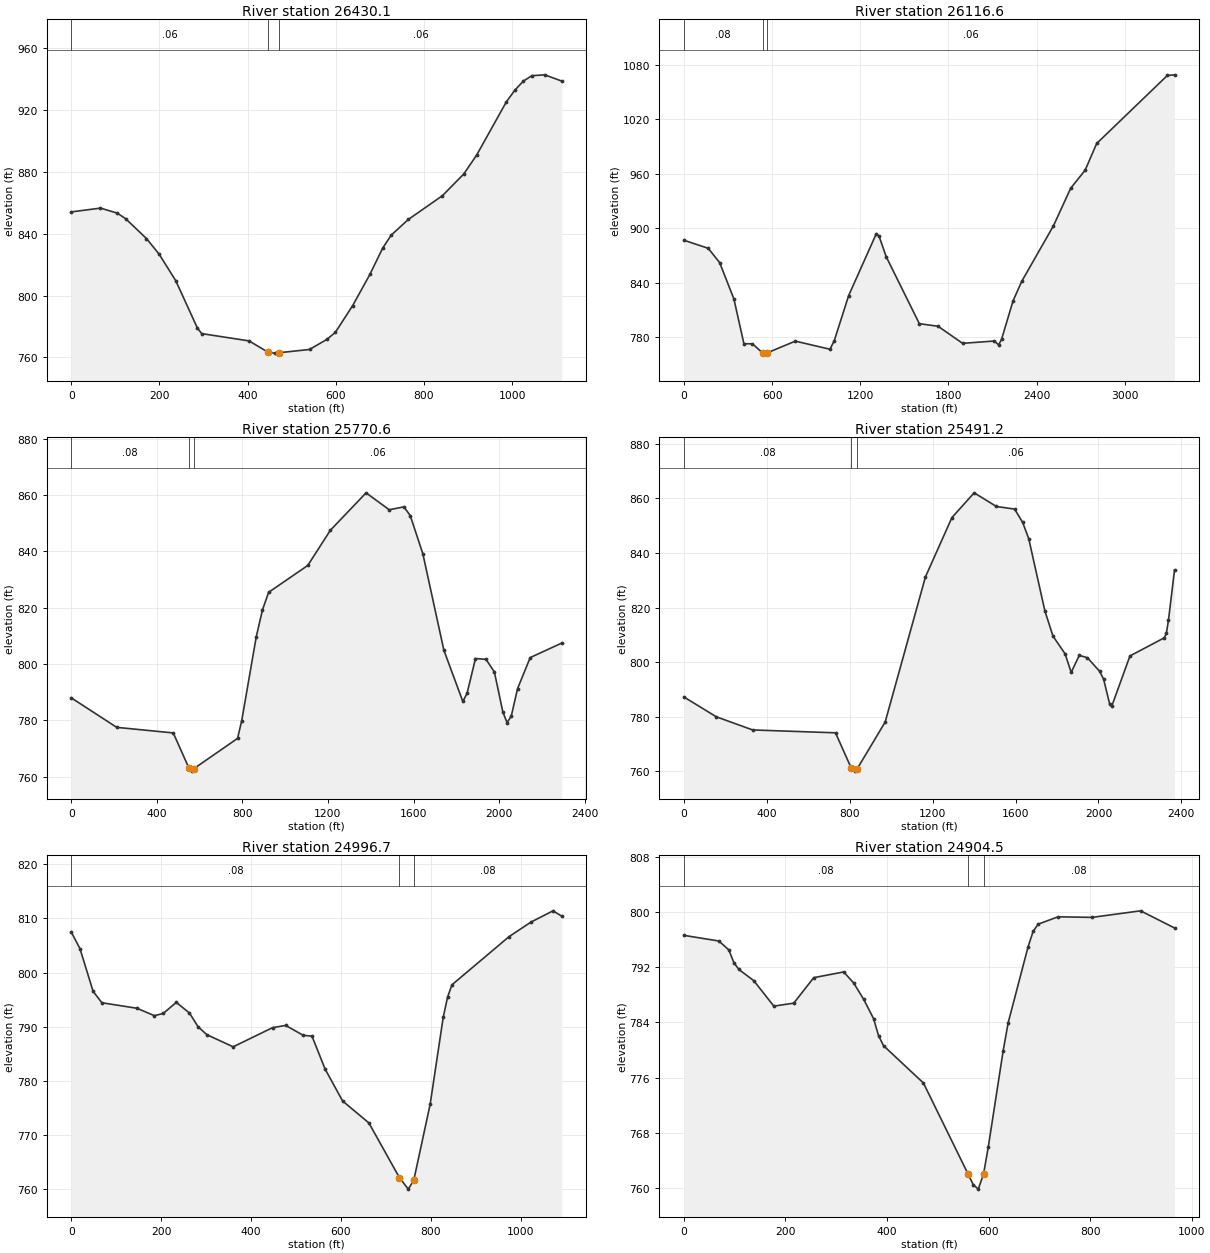
Type RM Length L Ch R = 1 ,26430.1 ,269.7,270.9,272
XS GIS Cut Line= 4
       1930397.6      569380.153      1930533.04      569574.708
     1930972.651      569600.192     1931383.858      569457.882
#Sta/Elev= 30
       0  854.11    66.4  856.57   104.3  853.34   123.3  849.77   170.7  836.88
   199.1  826.88   237.1  809.61     286  779.08   295.8  775.36   403.4  770.63
   446.6  763.28   461.6  762.72   471.9  762.99   540.4  765.09   579.6  771.56
   599.1  776.18   638.3  793.49   677.4  813.68   706.4  830.73   725.8  839.11
   764.4  849.21   841.8  864.61   890.1  878.62   919.2  890.78   986.8  925.33
  1006.2  932.94  1025.5  938.81  1044.8  942.29  1073.9  942.83  1112.5  938.77
#Mann= 3 , 0 , 0
       0     .06       0   446.6    .045       0   471.9     .06       0
Bank Sta=446.6,471.9
XS Rating Curve= 0 ,0
Exp/Cntr=0.3,0.1

Type RM Length L Ch R = 1 ,26116.6 ,341.7,346,350.3
XS GIS Cut Line= 5
     1930144.417       569779.05      1930452.48      569867.499
     1930878.074      569908.274     1931358.898      569585.839
     1932289.939      571368.636
#Sta/Elev= 30
       0   886.6   165.1  877.73   242.8     862   339.9  821.94     408  772.62
   466.3  772.59   535.1  762.46     544   762.3   563.4  762.39   757.9  775.51
   993.4  766.57  1022.8  776.01  1120.9  825.75  1307.4  893.28    1327  891.36
    1376  868.53  1601.7  794.73  1729.2  791.87    1896  773.08  2111.9  775.64
  2141.3  771.39  2160.9  777.48  2239.4  819.83  2298.3  841.32  2514.1  902.48
  2631.8  943.92    2730  963.77  2808.4  993.13  3289.2 1068.01  3338.2 1068.73
#Mann= 3 , 0 , 0
       0     .08       0   535.1    .045       0   563.4     .06       0
#XS Ineff= 2 , 0
       0                   767.7       0
Permanent Ineff=
       F       F
Bank Sta=535.1,563.4
XS Rating Curve= 0 ,0
Exp/Cntr=0.3,0.1

Type RM Length L Ch R = 1 ,25770.6 ,284.4,279.4,274.5
XS GIS Cut Line= 6
     1930120.187      570234.762     1930566.748      570204.622
     1930959.213      570314.206     1931094.281      570664.621
      1930899.04      571126.248      1930715.55       571656.33
#Sta/Elev= 30
       0  788.03   212.8  777.54     477  775.56   550.9  762.98   564.3     762
     574  762.91   777.7  773.63   797.1  779.93     865   809.7   893.8  819.18
   922.7  825.48  1105.7  835.01  1211.6  847.53  1378.3   860.8  1486.4  854.79
  1555.2  855.82  1584.7  852.72  1643.6  839.17  1741.9  804.92  1830.5  786.73
  1850.2   789.6  1889.6  801.97  1938.8   801.7  1978.1  797.18  2017.5  783.01
  2037.2   779.2  2056.8  781.52  2086.4  791.31  2145.4  802.31    2293  807.47
#Mann= 3 , 0 , 0
       0     .08       0   550.9    .045       0     574     .06       0
Bank Sta=550.9,574
XS Rating Curve= 0 ,0
Exp/Cntr=0.3,0.1

Type RM Length L Ch R = 1 ,25491.2 ,481.2,494.3,507.4
XS GIS Cut Line= 6
     1930122.736      570254.017     1930561.073      570232.355
     1930556.979      570505.554     1930901.306      570528.207
     1931064.832      570698.105     1930669.961      571696.893
#Sta/Elev= 30
       0  787.26     156  780.01   331.6  775.19   731.3  774.14     808  761.08
   827.1  760.11   836.7  761.06   970.9  778.08  1165.2  831.23    1293  852.96
  1400.3  862.02  1507.6  857.02  1595.3  856.07  1634.4  851.18  1663.6  845.25
  1741.6  818.77  1780.7  809.54  1839.2  803.06  1868.4  796.26  1907.5   802.5
  1946.7  801.64  2005.3   796.7  2024.9  793.81  2054.2  784.65    2064  783.84
    2152  802.28  2318.3  808.96  2328.1  810.74  2337.9  815.38  2367.2  833.79
#Mann= 3 , 0 , 0
       0     .08       0     808    .045       0   836.7     .06       0
Bank Sta=808,836.7
XS Rating Curve= 0 ,0
Exp/Cntr=0.3,0.1

Type RM Length L Ch R = 1 ,24996.7 ,92.9,92.3,91.7
XS GIS Cut Line= 4
     1929938.724      570518.157     1930165.023      570702.988
     1930654.352       571072.65     1930801.269      571186.393
#Sta/Elev= 30
       0  807.51    19.5  804.42    48.7  796.52    68.2   794.4   146.1  793.38
     185  792.01   204.5  792.41   233.8  794.47     263   792.5   282.4  789.94
   301.9  788.48   360.3  786.24   447.9  789.79   477.1   790.2   516.1  788.37
   535.6  788.22   564.8  782.11   603.7  776.21   662.1  772.15   730.2     762
   749.7  759.89  761.88   761.5   798.4  775.59   827.6  791.76   837.3  795.48
     847  797.73   973.9  806.64  1022.8  809.34  1071.7  811.42  1091.2  810.43
#Mann= 3 , 0 , 0
       0     .08       0   730.2    .045       0  761.88     .08       0
Bank Sta=730.2,761.88
XS Rating Curve= 0 ,0
Exp/Cntr=0.3,0.1

Type RM Length L Ch R = 1 ,24904.5 ,77.8,77.6,77.5
XS GIS Cut Line= 4
     1929986.094      570726.796     1930252.677      570893.855
     1930596.274      571139.112     1930758.594      571301.431
#Sta/Elev= 30
       0  796.63    68.8  795.81    88.5  794.51    98.3  792.67   108.2  791.68
   137.6  790.05     177  786.36   216.3  786.79   255.6  790.49   314.6  791.32
   334.2  789.73   353.9  787.36   373.5  784.54   383.3  782.07   393.1  780.62
   471.7   775.2     560  761.93   569.9  760.44   579.7   759.8   590.1  761.99
   599.3  765.85   628.8   779.9   638.6  783.95   677.8  794.96   687.7  797.19
   697.5  798.25   736.8  799.32   803.7  799.24   899.4  800.19   966.3   797.7
#Mann= 3 , 0 , 0
       0     .08       0     560    .045       0   590.1     .08       0
Bank Sta=560,590.1
XS Rating Curve= 0 ,0
Exp/Cntr=0.3,0.1

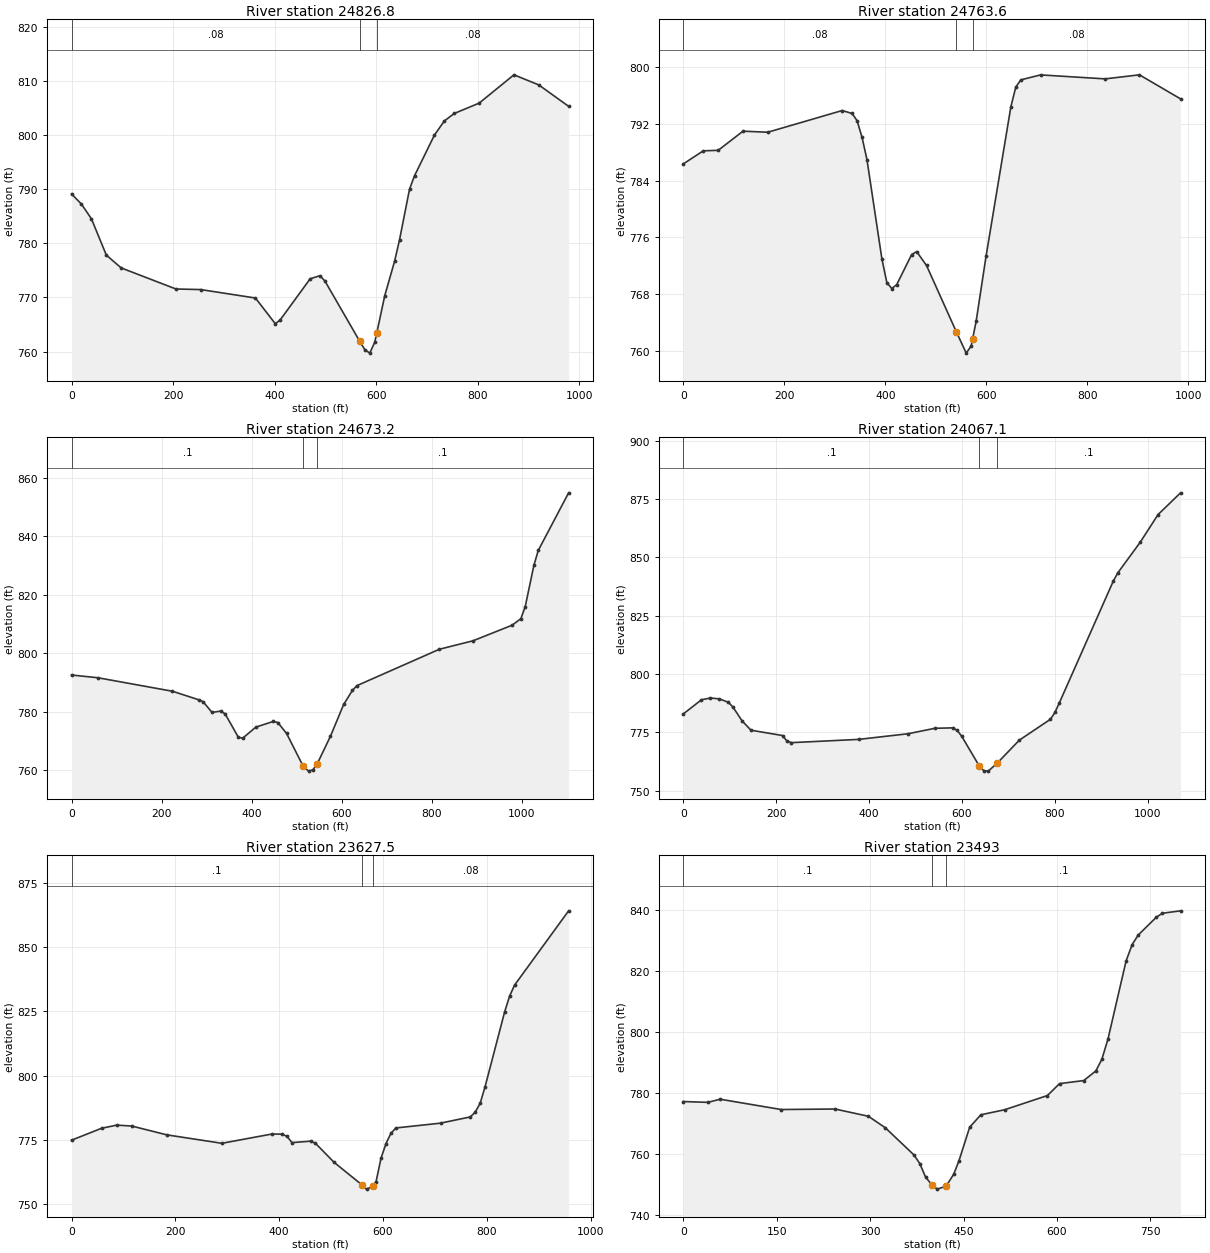
Type RM Length L Ch R = 1 ,24826.8 ,62.6,62.9,63.2
XS GIS Cut Line= 2
     1929933.336      570763.972     1930733.087      571329.129
#Sta/Elev= 30
       0  789.14    19.6  787.24    39.2  784.54    68.6  777.82    97.9  775.46
   205.6  771.57   254.6  771.46   362.3   769.9   401.5  765.15   411.3  765.88
   470.1  773.45   489.6  774.03   499.4  773.01     568  761.87   577.8  760.36
   587.6  759.72   597.4  761.75   601.3  763.41     617   770.3   636.5   776.7
   646.3   780.7   665.9  790.01   675.7  792.48   714.9  799.99   734.5  802.61
     754  803.99     803   805.9   871.6  811.13   920.5  809.27   979.3  805.31
#Mann= 3 , 0 , 0
       0     .08       0     568    .045       0   601.3     .08       0
#XS Ineff= 2 , 0
       0   479.8                       0
Permanent Ineff=
       F       F
Bank Sta=568,601.3
XS Rating Curve= 0 ,0
Exp/Cntr=0.3,0.1

Type RM Length L Ch R = 1 ,24763.6 ,90.9,90.7,90.6
XS GIS Cut Line= 3
     1929913.589      570811.562     1930633.957       571340.78
     1930698.551      571404.058
#Sta/Elev= 30
       0  786.38    39.3  788.21    68.8  788.28   117.9  790.98     167  790.83
   314.3  793.89     334  793.47   343.8  792.45   353.6  790.11   363.4  786.95
   392.9  772.98   402.7  769.64   412.6   768.8   422.4  769.37   451.8  773.59
   461.7  774.01   481.3  772.05   540.2  762.72   559.9   759.7   569.7  760.71
   572.6  761.73   579.5  764.17   599.2  773.37   648.3  794.42   658.1   797.2
     668  798.21   707.2  798.91   834.9  798.35   902.9  798.92   984.3  795.53
#Mann= 3 , 0 , 0
       0     .08       0   540.2    .045       0   572.6     .08       0
#XS Ineff= 2 , 0
       0   461.7                       0
Permanent Ineff=
       F       F
Bank Sta=540.2,572.6
XS Rating Curve= 0 ,0
Exp/Cntr=0.3,0.1

Type RM Length L Ch R = 1 ,24673.2 ,582,606,629.9
XS GIS Cut Line= 4
     1929869.103      570887.338     1930489.946      571343.887
     1930575.253      571430.774      1930527.86      571637.722
#Sta/Elev= 30
       0  792.51    58.5  791.57   224.4  786.95   282.9  784.02   292.6  783.34
   312.2  779.71   331.7  780.16   341.4   779.2   370.7  771.23   380.4  770.89
   409.7  774.68   448.7  776.64   458.5  776.24     478   772.5  514.89  761.28
   526.8  759.62   536.5  760.09   546.3   762.2   575.5  771.58   604.8  782.44
   624.3  787.25   634.1  788.86   817.5  801.32   892.4  804.22   979.2  809.55
   998.6  811.78  1008.2  815.85  1027.5  829.99  1037.2  835.12  1104.7  854.84
#Mann= 3 , 0 , 0
       0      .1       0  514.89    .045       0   546.3      .1       0
#XS Ineff= 2 , 0
       0   448.7                       0
Permanent Ineff=
       F       F
Bank Sta=514.89,546.3
XS Rating Curve= 0 ,0
Exp/Cntr=0.3,0.1

Type RM Length L Ch R = 1 ,24067.1 ,370.7,439.5,498.3
XS GIS Cut Line= 5
     1929728.758      570835.259     1929899.371      570963.219
     1929752.454      571245.995     1929718.803      571540.853
     1929611.856      571757.835
#Sta/Elev= 30
       0  782.96    38.8  788.97    58.2  789.73    77.6  789.34    96.9  787.87
   106.6  785.84     126  779.99   145.4  775.93   213.3  773.65   222.9  771.26
   232.6   770.6   377.4     772   483.6  774.41   541.5  776.75   579.8  776.94
   589.4  775.87   598.9  773.45   637.2  760.57   646.8  758.58   656.4   758.4
   675.5  761.78   723.4  771.68   790.4  780.62     800  783.54   809.6  787.67
   925.5  839.71   935.1  843.25   983.5   856.4  1022.2  868.33  1070.6  877.63
#Mann= 3 , 0 , 0
       0      .1       0   637.2    .045       0   675.5      .1       0
Bank Sta=637.2,675.5
XS Rating Curve= 0 ,0
Exp/Cntr=0.3,0.1

Type RM Length L Ch R = 1 ,23627.5 ,150.5,134.6,138.1
XS GIS Cut Line= 6
     1929598.033      570846.514     1929496.139       571258.83
      1929361.07      571188.926      1929299.46      571143.903
     1929216.523      571064.521     1929109.889      571220.916
#Sta/Elev= 30
       0   774.9    57.9  779.55    86.9  780.76   115.8  780.43   183.4  776.99
   289.6   773.7   386.1  777.31   405.4  777.26   415.1  776.37   424.7  773.96
   460.8  774.53   469.8  773.71   505.7   766.3   559.2  757.55   568.2  755.86
     580   756.9   586.6  758.79   596.2   767.9   605.7  773.58   615.2  777.58
   624.8  779.67   710.8  781.54   768.2  783.97   777.7  785.86   787.1  789.25
   796.6  795.72   834.4  824.93   843.9  831.02   853.4  835.27   957.5  864.18
#Mann= 3 , 0 , 0
       0      .1       0   559.2    .045       0     580     .08       0
Bank Sta=559.2,580
XS Rating Curve= 0 ,0
Exp/Cntr=0.3,0.1

Type RM Length L Ch R = 1 ,23493   ,440.5,401.2,352.6
XS GIS Cut Line= 6
      1929555.38      570922.343       1929491.4      571128.501
     1929472.443      571148.642     1929324.341      571058.596
     1929207.044       570938.93     1929071.975      571104.804
#Sta/Elev= 30
       0  777.07    39.2   776.8    58.9  777.83     157  774.45   243.5  774.62
   297.1  772.24   324.2  768.49   370.3  759.56   379.7  756.73     389  752.28
     400 749.581   407.8  748.36     422 749.364   434.2  753.25   442.7  757.71
   459.8  768.66   477.8  772.73     516  774.38   584.7  779.04   604.2  782.94
   643.1  783.95   662.5   787.1   672.2  790.93     682  797.55   711.1  823.16
   720.8  828.51   730.6  831.65   759.7  837.49   769.5  838.79   798.6  839.58
#Mann= 3 , 0 , 0
       0      .1       0     400    .045       0     422      .1       0
Bank Sta=400,422
XS Rating Curve= 0 ,0
Exp/Cntr=0.3,0.1

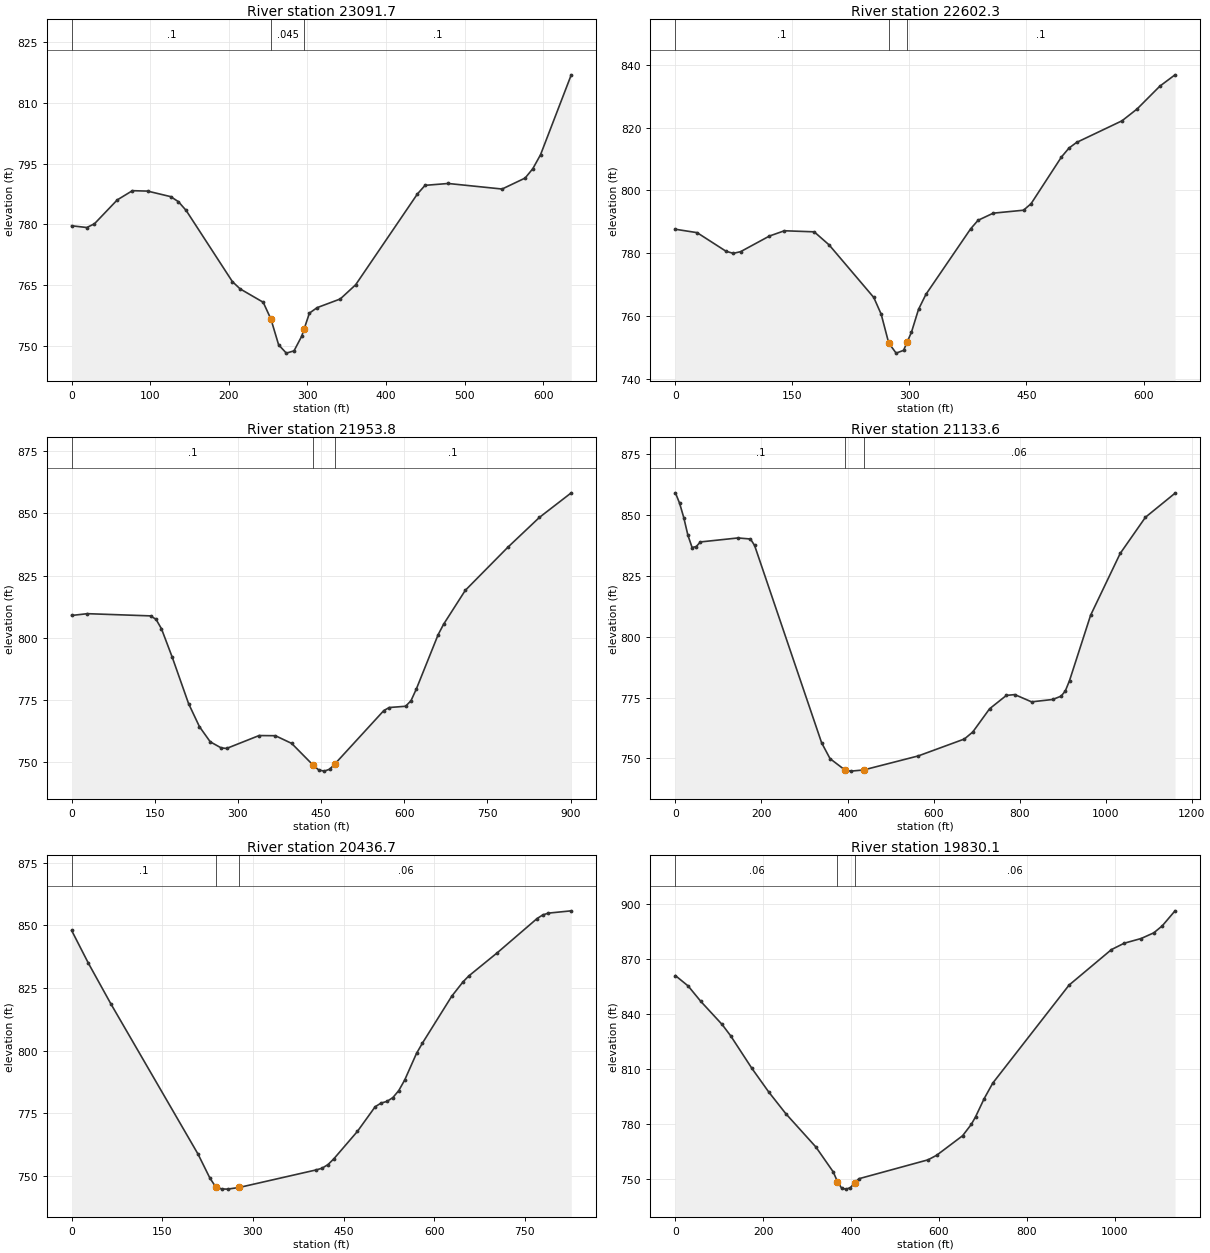
Type RM Length L Ch R = 1 ,23091.7 ,500.9,489.5,478.1
XS GIS Cut Line= 4
     1929340.533      570456.249     1929313.151      570548.928
     1929028.795      570873.304     1928929.797      570915.431
#Sta/Elev= 30
       0  779.67    19.3  779.24      29  780.16      58  786.06    77.3  788.34
    96.6  788.24     126  786.87   135.8  785.63   145.7  783.45   204.5  765.87
   214.3  764.08   243.7  760.77   253.5  756.62   263.3  750.26   273.1   748.2
   282.9  748.76   292.7  752.39   295.9  754.25   302.5  758.09   312.3  759.44
   341.7  761.58   361.3  765.09   439.8  787.51   449.6  789.66     479  790.12
   547.6  788.75   576.9  791.46   586.7  793.78   596.5  797.22   635.6  816.97
#Mann= 3 , 0 , 0
       0      .1       0   253.5    .045       0   295.9      .1       0
Bank Sta=253.5,295.9
XS Rating Curve= 0 ,0
Exp/Cntr=0.3,0.1

Type RM Length L Ch R = 1 ,22602.3 ,652.6,648.4,644.2
XS GIS Cut Line= 4
     1928853.969      570199.276     1928803.417      570308.806
     1928746.546      570569.992     1928668.611      570810.114
#Sta/Elev= 30
       0  787.63    27.8  786.55      65   780.6    74.2  779.96    83.5  780.48
   120.6  785.48   139.7  787.15   177.9  786.81     197  782.65   254.3  765.88
   263.8  760.53   273.4   751.4   282.9  748.15   292.5  749.04  296.91  751.62
   302.5  754.76   311.6  762.09   321.1  766.88   378.4  787.76   387.9  790.48
   407.4  792.76   446.2   793.7   455.9  795.78   494.8  810.65   504.5  813.51
   514.2   815.3   572.4  822.19   591.8  825.97     621  833.25   640.4  836.85
#Mann= 3 , 0 , 0
       0      .1       0   273.4    .045       0  296.91      .1       0
Bank Sta=273.4,296.91
XS Rating Curve= 0 ,0
Exp/Cntr=0.3,0.1

Type RM Length L Ch R = 1 ,21953.8 ,822.4,819.8,817.2
XS GIS Cut Line= 4
     1928160.984      570034.982     1928137.814      570165.575
     1928125.176      570742.711     1928064.092      570923.857
#Sta/Elev= 30
       0  808.91    28.4  809.63   142.4  808.74   152.2  807.35     162  803.56
   181.6  791.99   210.9  773.41   230.5  764.13     250  758.02   269.6  755.59
   279.4  755.35   338.1  760.55   367.5  760.48   396.8  757.39     436  748.52
   445.7  746.68   455.5  746.22   465.3  746.98   475.1  749.19   563.1  770.63
   572.9  771.84   602.3  772.34   612.1   774.6   621.8  779.36     661  801.17
   670.8  805.36   709.9     819   786.4  836.31   843.7  848.41   901.1   858.3
#Mann= 3 , 0 , 0
       0      .1       0     436    .045       0   475.1      .1       0
#XS Ineff= 2 , 0
       0   347.9                       0
Permanent Ineff=
       F       F
Bank Sta=436,475.1
XS Rating Curve= 0 ,0
Exp/Cntr=0.3,0.1

Type RM Length L Ch R = 1 ,21133.6 ,706,696.8,687.6
XS GIS Cut Line= 4
     1927354.256      569921.239     1927335.299      570152.937
      1927375.32      570746.924     1927590.166      571001.791
#Sta/Elev= 30
       0   859.2     9.7  854.94    19.4  849.04    29.1  841.73    38.8  836.72
    48.4  837.12    58.1  839.01   145.3  840.65   174.4  840.22     184  837.59
   339.8  756.46   359.4  749.93     395 745.136   408.1   744.8   437.4  745.28
   564.3  751.04   671.6     758   691.2   760.9   730.2  770.43   769.2  775.92
   788.8  776.26   827.8  773.28   876.8  774.25   896.4  775.62   906.2  777.74
     916  782.02   965.1  808.92  1033.7  834.26  1092.5  849.16  1161.2  859.04
#Mann= 3 , 0 , 0
       0      .1       0     395    .045       0   437.4     .06       0
Bank Sta=395,437.4
XS Rating Curve= 0 ,0
Exp/Cntr=0.3,0.1

Type RM Length L Ch R = 1 ,20436.7 ,598.7,606.5,614.3
XS GIS Cut Line= 4
     1926629.676      570359.358     1926694.972      570437.292
     1926937.005       570895.17     1927061.475      571060.769
#Sta/Elev= 30
       0  847.92    27.7  834.87    64.7  818.74   209.2   758.7   228.7   749.2
   238.5   745.6   248.2  744.83     258  744.75   277.6  745.43   404.6  752.41
   414.4  753.09   424.2  754.54   433.9  756.84     473  767.81   502.3  777.62
   512.1  779.08   521.9  779.75   531.6  781.27   541.4  784.08   551.2   788.3
   570.7  798.89   580.5  802.99     629   821.7   647.8  827.46   657.2  829.78
   704.3  839.02   770.2  852.68   779.7  854.13   789.1  854.85   826.8  855.76
#Mann= 3 , 0 , 0
       0      .1       0   238.5    .045       0   277.6     .06       0
Bank Sta=238.5,277.6
XS Rating Curve= 0 ,0
Exp/Cntr=0.3,0.1

Type RM Length L Ch R = 1 ,19830.1 ,710.3,747.7,785.1
XS GIS Cut Line= 4
     1926320.044      570443.611     1926254.747      570696.372
     1926320.044      571153.447     1926151.537      571532.588
#Sta/Elev= 30
       0  861.02      29  855.37      58  846.92   106.4  834.38   125.7  828.26
     174  810.55   212.7  797.56   251.4  785.81     320  767.62   359.3  754.13
   369.1  748.78   378.9  745.08   388.8   744.7   398.6   745.5   408.4  748.31
   418.2  750.39   575.4  760.67   595.1  763.18     654  773.79   673.7  779.95
   683.5  784.09   703.1     794   722.8   802.5   896.4  855.84   992.9  875.18
  1021.9  878.65  1060.5  881.22  1089.4  884.32  1108.7  888.14  1137.7   896.3
#Mann= 3 , 0 , 0
       0     .06       0   369.1    .045       0   408.4     .06       0
Bank Sta=369.1,408.4
XS Rating Curve= 0 ,0
Exp/Cntr=0.3,0.1

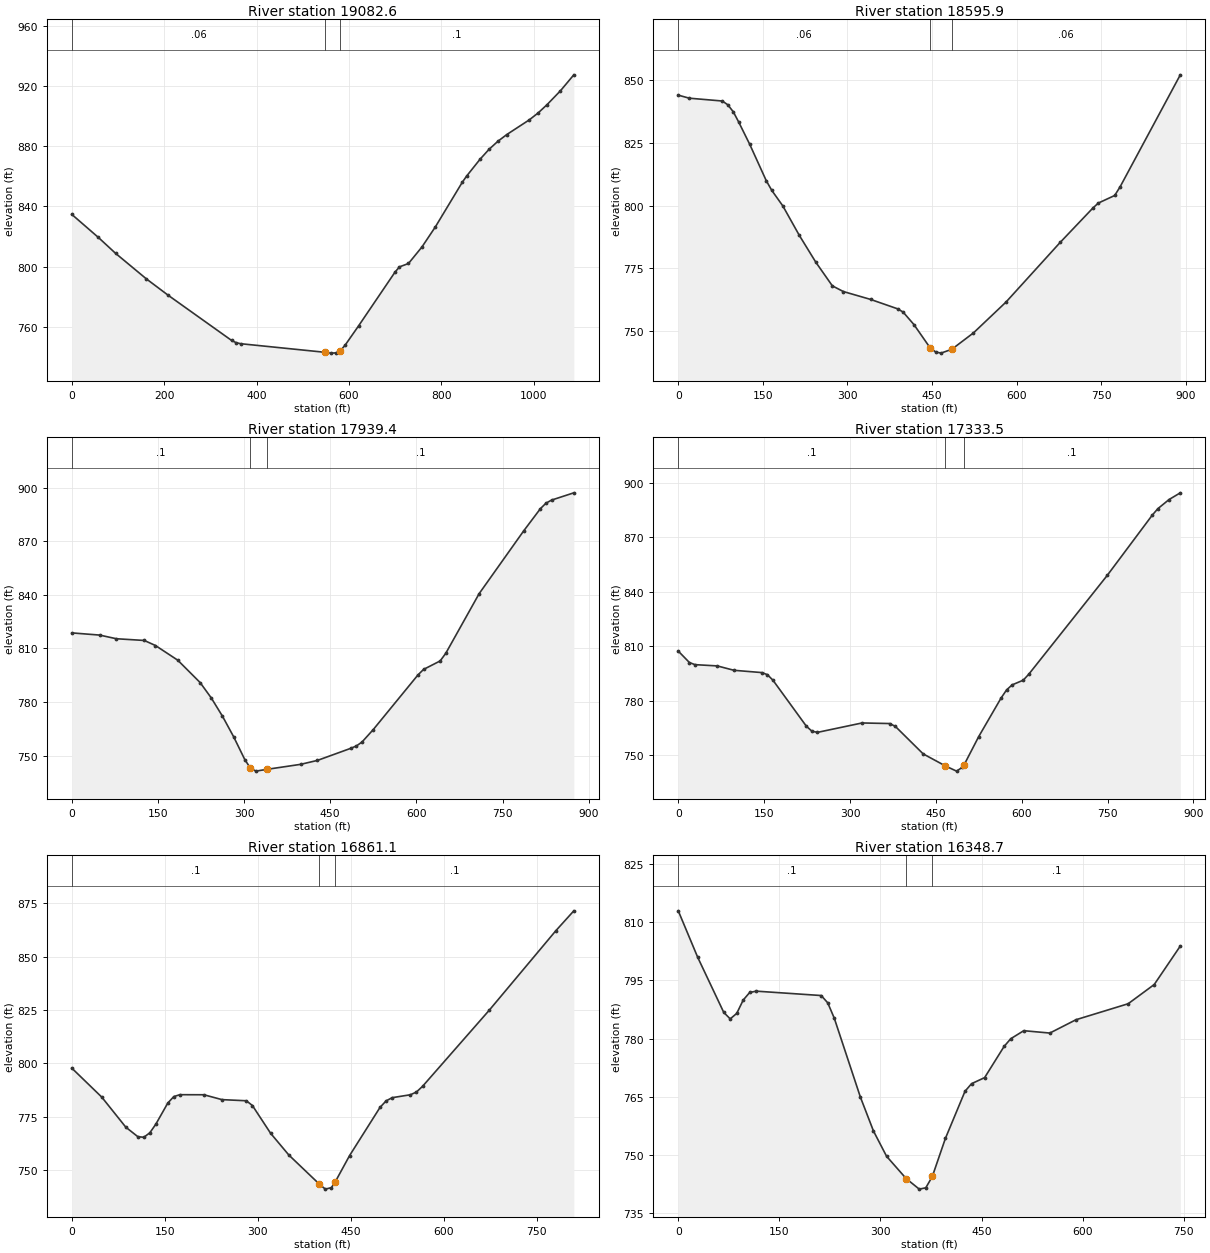
Type RM Length L Ch R = 1 ,19082.6 ,498.5,486.3,474.1
XS GIS Cut Line= 4
     1926219.763       570404.48     1926091.802      570581.412
     1925572.063      570605.108     1925341.419      570865.768
#Sta/Elev= 30
       0  834.67      57  819.51    94.9  808.79   161.4  791.87   208.9  780.93
     346  750.98   355.8  749.51   365.6  748.82   549.1  743.09   561.9  742.57
   571.8  742.74   581.6   744.3   591.4  747.74   620.8  760.65   699.4  796.22
   709.2  799.81   728.8  802.06     758  813.04     787  826.36     845  855.84
   854.6  860.06   883.7  871.25     903  877.78   922.3  883.17   941.7  887.67
     990  897.33  1009.3  901.94  1028.7  907.47  1057.7  916.68  1086.7  927.29
#Mann= 3 , 0 , 0
       0     .06       0   549.1    .045       0   581.6      .1       0
Bank Sta=549.1,581.6
XS Rating Curve= 0 ,0
Exp/Cntr=0.3,0.1

Type RM Length L Ch R = 1 ,18595.9 ,682.1,656.4,630.8
XS GIS Cut Line= 4
     1926191.327      569846.826     1925954.364      570034.817
     1925627.355      570254.403     1925474.119      570372.884
#Sta/Elev= 30
       0  843.85    19.5  842.64    78.1  841.52    87.8  840.02    97.6  837.22
   107.3   833.1   126.8  824.27   156.1  809.83   165.9  805.99   185.4  799.84
   214.7  788.12   243.9  777.48   273.2   768.1   292.7  765.84   340.9  762.72
   388.9  758.98   398.6   757.7   417.8  752.73   446.6  743.46   456.2  741.86
   465.8  741.38     485  742.91   523.4  749.42   581.1  761.67   677.2  785.38
   735.1  799.01   744.8  800.99   773.8     804   783.5   807.5   890.1  851.92
#Mann= 3 , 0 , 0
       0     .06       0   446.6    .045       0     485     .06       0
Bank Sta=446.6,485
XS Rating Curve= 0 ,0
Exp/Cntr=0.3,0.1

Type RM Length L Ch R = 1 ,17939.4 ,604.5,605.7,606.9
XS GIS Cut Line= 4
     1925260.852      569608.284     1925205.561      569774.158
     1925267.171      570197.532       1925210.3       570462.93
#Sta/Elev= 30
       0  818.68    48.6  817.45    77.7   815.4   126.3  814.44   145.7  811.61
   184.6  803.38   223.5  790.86   242.9  782.25   262.4  772.02   281.8  760.54
   301.2  747.78     311  742.97   320.7  741.28   340.2   742.3   398.5  745.08
   427.7  747.28     486  754.08   495.7   755.4   505.4   757.6   524.9  764.54
   602.7  795.12   612.4  798.21   641.4  802.98   651.2  807.27   709.3  840.67
   786.9  875.83   815.9  888.22   825.6   891.3   835.3  893.03   874.1   897.1
#Mann= 3 , 0 , 0
       0      .1       0     311    .045       0   340.2      .1       0
Bank Sta=311,340.2
XS Rating Curve= 0 ,0
Exp/Cntr=0.3,0.1

Type RM Length L Ch R = 1 ,17333.5 ,486.8,472.4,457.9
XS GIS Cut Line= 4
     1924701.619      569684.112      1924692.14      569995.323
     1924717.417      570304.955     1924846.956      570524.541
#Sta/Elev= 30
       0  807.38    19.5  801.08    29.2  799.91    68.1  799.22    97.3   796.8
     146  795.54   155.7  794.39   165.4  791.34   223.8  765.98   233.5  763.24
   243.2   762.6   321.1  767.78   369.6  767.46   379.3  765.86   427.8  750.74
   466.7   744.1   486.1  741.24   495.8  743.25  499.33  744.71   524.9  760.31
   563.8  781.46   573.5  785.99   583.2  788.76   602.6  791.35   612.3  794.64
   749.5  849.15   827.9  882.25   837.7  885.84   857.4  890.91     877  894.59
#Mann= 3 , 0 , 0
       0      .1       0   466.7    .045       0  499.33      .1       0
Bank Sta=466.7,499.33
XS Rating Curve= 0 ,0
Exp/Cntr=0.3,0.1

Type RM Length L Ch R = 1 ,16861.1 ,518.3,512.1,505.9
XS GIS Cut Line= 4
     1924088.674      569914.756     1924126.589      570134.342
      1924373.03      570413.958     1924507.309      570581.412
#Sta/Elev= 30
       0  797.85    48.4  784.27    87.2   770.2   106.6  765.76   116.3  765.47
     126  767.58   135.6  771.58     155   781.5   164.7  784.52   174.4   785.4
   213.2  785.37   242.4  783.09   281.7  782.56   291.5  780.34   320.9  767.34
   350.3  757.17   399.4  743.59   409.2  741.21   418.9   741.9  424.74  744.38
   448.4  756.94   497.5  779.48   507.3  782.51   517.1  784.01   546.5  785.37
   556.3  786.67   566.1  789.32   673.6  824.89   780.9  862.04   810.2  871.44
#Mann= 3 , 0 , 0
       0      .1       0   399.4    .045       0  424.74      .1       0
Bank Sta=399.4,424.74
XS Rating Curve= 0 ,0
Exp/Cntr=0.3,0.1

Type RM Length L Ch R = 1 ,16348.7 ,409.8,398.2,386.6
XS GIS Cut Line= 4
     1923657.402      570429.756      1923793.26      570579.832
     1924046.021      570742.547     1924278.245      570810.476
#Sta/Elev= 30
       0  812.97    28.9  800.96    67.5  786.77    77.1  785.09    86.8  786.52
    96.4  789.96     106  791.91   115.7  792.25   212.1  791.12   221.8  789.24
   231.5  785.28   270.3   764.9   289.7  756.16   309.1  749.66   338.2   743.9
   357.6  741.18   367.3  741.52     377  744.44   396.4  754.26   425.5  766.42
   435.2  768.38   454.6  769.94   483.6  778.01   493.4  779.98   512.7  782.05
   551.4  781.44   590.2  784.88   667.6     789   706.3  793.96     745  803.89
#Mann= 3 , 0 , 0
       0      .1       0   338.2    .045       0     377      .1       0
Bank Sta=338.2,377
XS Rating Curve= 0 ,0
Exp/Cntr=0.3,0.1

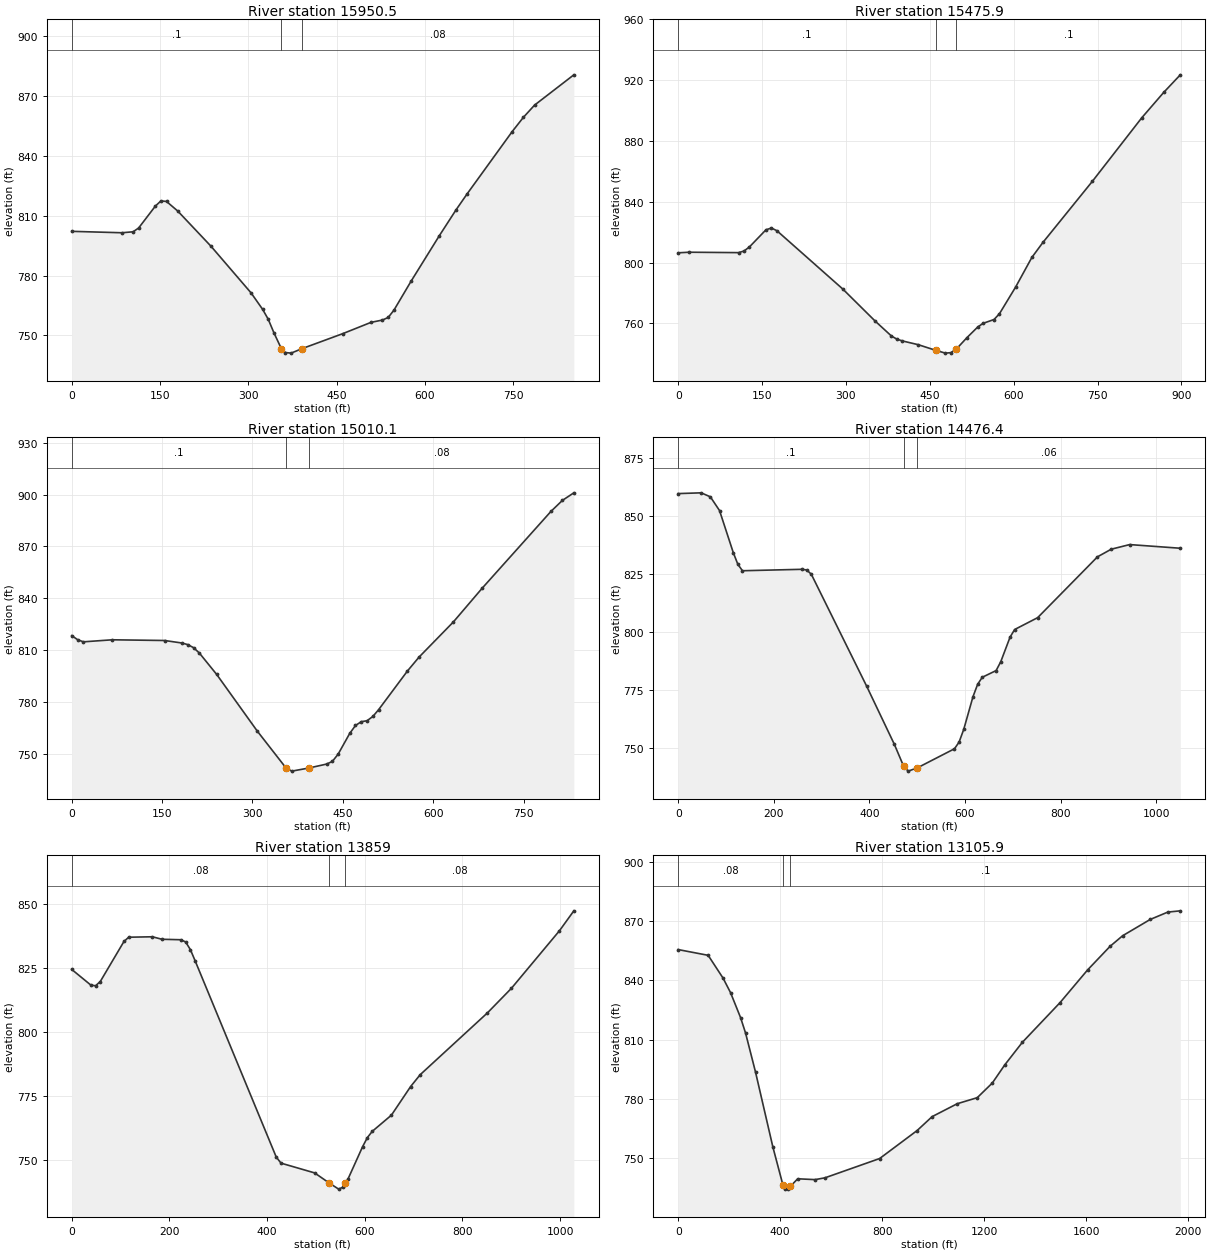
Type RM Length L Ch R = 1 ,15950.5 ,450.6,474.5,498.3
XS GIS Cut Line= 4
     1923398.322      570898.943      1923606.85      571011.105
     1923965.454      571031.642     1924203.997      571128.007
#Sta/Elev= 30
       0  802.15    85.2  801.44   104.2  801.92   113.6  803.81   142.1  814.81
   151.5  817.38     161  817.12     180  812.34   236.8  794.62   304.7  771.32
   324.2  763.14   333.9   758.1   343.6  751.28  356.13  743.42     363  741.44
   372.7  741.15   391.7  743.44   460.1  750.86   508.6  756.57     528  757.72
   537.7  759.02   547.4  762.63   576.6  777.17   624.6  799.96   653.1  812.95
   672.2  821.06   748.4   852.1   767.5  859.26   786.5  865.38   853.2  880.54
#Mann= 3 , 0 , 0
       0      .1       0  356.13    .045       0   391.7     .08       0
Bank Sta=356.13,391.7
XS Rating Curve= 0 ,0
Exp/Cntr=0.3,0.1

Type RM Length L Ch R = 1 ,15475.9 ,472.6,465.8,458.9
XS GIS Cut Line= 4
     1923243.506      571058.498     1923470.991      571244.909
     1923621.067      571548.221     1923869.089      571643.007
#Sta/Elev= 30
       0  806.39    19.6  806.77   107.8   806.5   117.6  807.55   127.4  810.27
   156.9  821.52   166.7  822.69   176.5  820.91   294.1  782.63   352.1  761.51
   381.1  751.72   390.8  749.63   400.5  748.45   429.5  745.92   460.8   742.2
   477.8  740.39   487.5  740.69   497.2  742.98   516.5  750.62   535.8  757.62
   545.5  760.02   564.8   762.5   574.5  766.29   603.5  783.89   632.5  803.36
   652.2  813.18   740.7  853.41   829.2  895.27   868.5  911.98     898  923.47
#Mann= 3 , 0 , 0
       0      .1       0   460.8    .045       0   497.2      .1       0
Bank Sta=460.8,497.2
XS Rating Curve= 0 ,0
Exp/Cntr=0.3,0.1

Type RM Length L Ch R = 1 ,15010.1 ,536.9,533.7,530.5
XS GIS Cut Line= 4
     1922955.991      571346.013     1923076.052      571565.599
     1923301.957      571800.982      1923542.08      571892.608
#Sta/Elev= 30
       0  818.48     9.6  816.16    19.2   814.9    67.4  816.08     154  815.67
   182.9  814.22   192.5   813.3   202.1  811.54   211.8  808.43   240.6  796.05
   307.8   763.4   355.8  741.96   365.4  740.19   394.2  742.03     423  744.26
   432.6   745.8   442.2     750   461.4  761.96     471  766.56   480.6  768.76
   490.2  769.31   499.8  771.77   509.4   775.7   557.3  798.07   576.5  806.07
   633.6  826.43   681.2  845.84   795.4  890.23   814.5  896.63   833.5     901
#Mann= 3 , 0 , 0
       0      .1       0   355.8    .045       0   394.2     .08       0
Bank Sta=355.8,394.2
XS Rating Curve= 0 ,0
Exp/Cntr=0.3,0.1

Type RM Length L Ch R = 1 ,14476.4 ,617.4,617.5,617.6
XS GIS Cut Line= 4
     1922489.964      571693.559     1922684.273      571955.798
     1922989.166      572194.341     1923297.998      572329.102
#Sta/Elev= 30
       0  859.58      48  859.91    67.2  858.19    86.4  852.28   115.2  834.17
   124.8  829.11   134.4  826.38   259.2     827   268.8  826.71   278.4  824.89
   394.1  776.76   452.2  751.67   471.6  742.25   481.2  740.15   500.6  741.59
     578  749.78   587.7  752.67   597.4  758.14   616.7  772.17   626.4  777.49
   636.1  780.54   665.1  783.42   674.8  787.22   694.2  797.77   703.8  801.08
     752  806.19   877.2  832.37     906  835.65   944.6  837.64  1050.5  836.06
#Mann= 3 , 0 , 0
       0      .1       0   471.6    .045       0   500.6     .06       0
Bank Sta=471.6,500.6
XS Rating Curve= 0 ,0
Exp/Cntr=0.3,0.1

Type RM Length L Ch R = 1 ,13859   ,773.8,752.4,727.4
XS GIS Cut Line= 4
     1922066.004      572236.693     1922331.988      572448.681
     1922625.822      572679.325     1922932.295      572750.414
#Sta/Elev= 30
       0  824.33    38.9  818.25    48.6  817.95    58.3  819.59   106.9  835.27
   116.6  836.93   165.2   837.1   184.6  836.13   223.5  835.94   233.2  835.08
     243  832.06   252.7  827.69   418.8  751.02   428.6  748.65   497.4  744.84
   526.9  740.94   546.6   738.5   556.4  739.35   560.4  740.82   566.2  742.64
   595.7  755.11   605.5  758.66   615.4  761.07   654.7  767.41     694  778.58
   713.7  783.23   851.3  807.36   900.5  816.98   998.8  839.45  1028.3  847.24
#Mann= 3 , 0 , 0
       0     .08       0   526.9    .045       0   560.4     .08       0
Bank Sta=526.9,560.4
XS Rating Curve= 0 ,0
Exp/Cntr=0.3,0.1

Type RM Length L Ch R = 1 ,13105.9 ,538,553.7,574
XS GIS Cut Line= 4
     1921635.317      573214.862     1921888.077      573243.297
     1922471.006      573085.322      1923579.82      573158.212
#Sta/Elev= 30
       0  855.59   117.4  852.69   176.1   841.1   205.4  833.75   244.6  821.15
   264.1  813.37   303.1  793.66   371.2  755.74   410.2  736.72     420  734.48
   429.7  734.41   439.4  735.76   468.7  739.64   536.8  739.22   575.8  740.14
   790.1  749.89     937  764.04     996  771.09  1094.3  777.61    1173  780.68
    1232  788.08  1281.2  797.32    1350   808.7  1497.5  828.73  1605.7  845.29
  1694.2  857.27  1743.3   862.6  1851.5  870.84  1920.4  874.56  1969.5   875.2
#Mann= 3 , 0 , 0
       0     .08       0   410.2    .045       0   439.4      .1       0
Bank Sta=410.2,439.4
XS Rating Curve= 0 ,0
Exp/Cntr=0.3,0.1

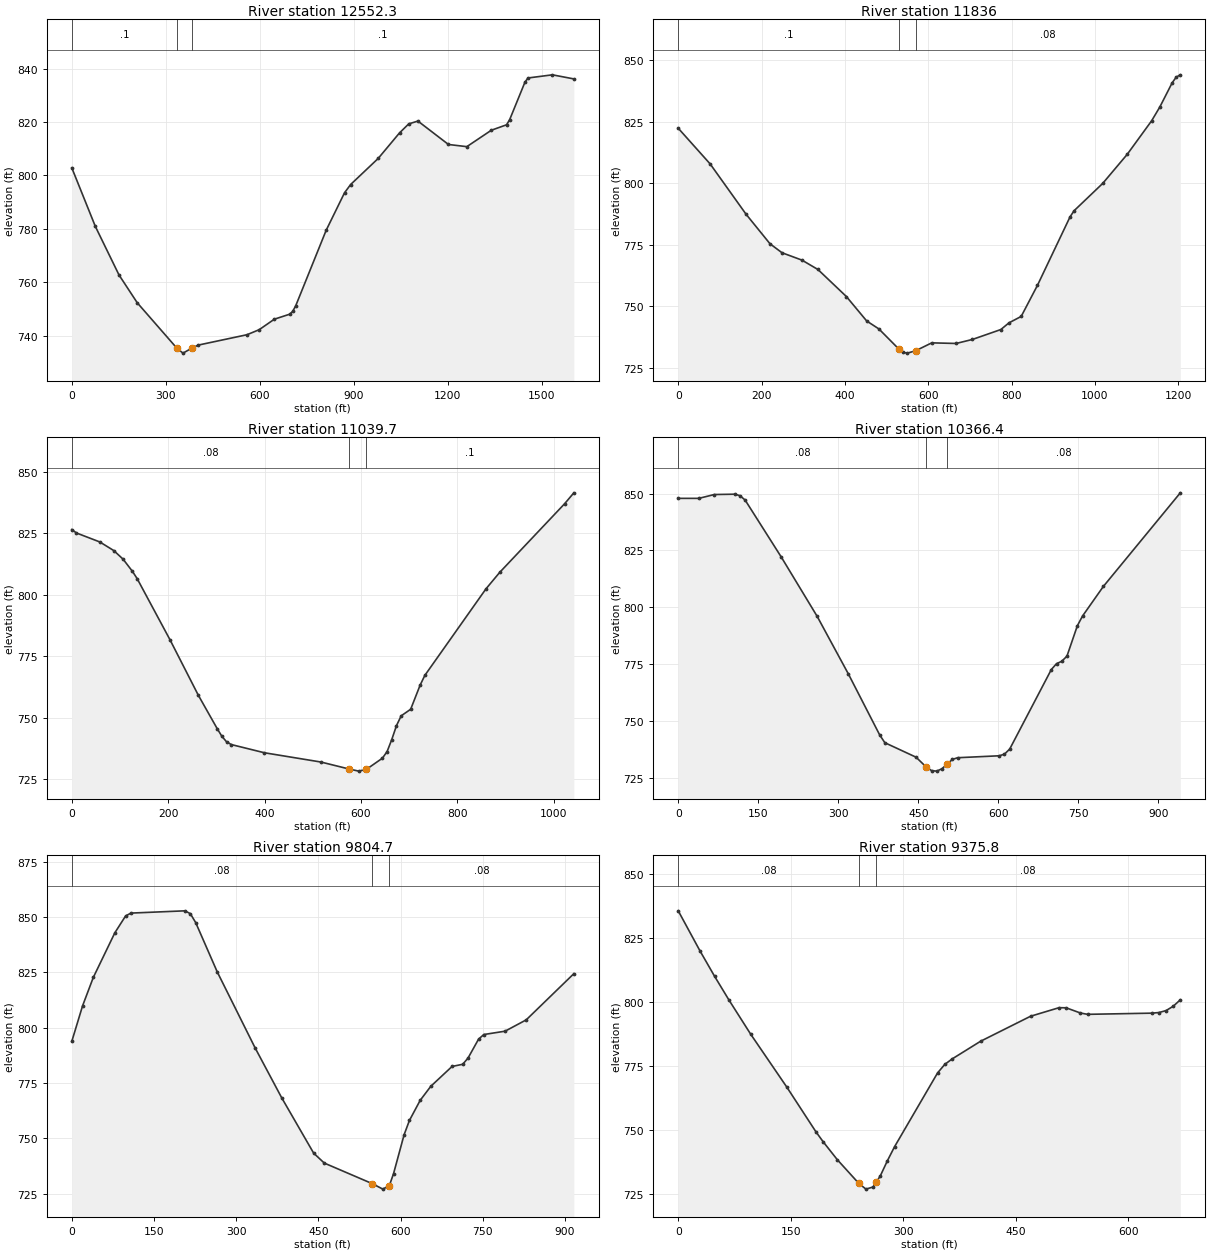
Type RM Length L Ch R = 1 ,12552.3 ,690.6,716,741.5
XS GIS Cut Line= 4
     1921889.657      573601.902     1922020.777       573676.15
     1922666.896      573759.877     1923466.554      573785.702
#Sta/Elev= 30
       0  802.88    75.3  780.92   150.7  762.79     209  752.37   335.4  735.39
   354.9  733.54   384.1  735.45   403.5  736.54   559.1  740.42     598   742.3
   646.6  746.24   695.2  748.09     705  749.15   714.7  751.25     812  779.53
   870.5  793.53     890  796.62   977.8  806.36  1046.1  815.94  1075.4   819.3
  1104.7  820.35  1202.2  811.59  1260.8  810.78  1338.8  816.91  1387.6  818.96
  1397.4  820.86  1446.2  834.89  1455.9  836.47    1534  837.65  1602.3  836.12
#Mann= 3 , 0 , 0
       0      .1       0   335.4    .045       0   384.1      .1       0
Bank Sta=335.4,384.1
XS Rating Curve= 0 ,0
Exp/Cntr=0.3,0.1

Type RM Length L Ch R = 1 ,11836   ,798.1,796.1,793.6
XS GIS Cut Line= 4
     1921448.906      573721.963     1921704.826      573938.389
     1921916.513      574494.462     1922095.025       574702.99
#Sta/Elev= 30
       0  822.36    76.6  807.84   162.8  787.37   220.2  775.36     249  771.71
   296.9  768.71   335.2   764.9   403.4  753.91   452.2  743.96   481.5  740.72
   530.2  732.39     540  731.19   549.8  730.88   569.3  731.82   608.3  735.06
   666.8  734.81   705.8  736.44   774.1  740.48   793.6   743.2   822.9  745.81
   861.9  758.45     940  786.27   949.8   788.8  1018.4   799.9  1077.2  811.72
    1136  825.42  1155.6  831.02  1185.1  840.83  1194.9  843.15  1204.7  844.09
#Mann= 3 , 0 , 0
       0      .1       0   530.2    .045       0   569.3     .08       0
Bank Sta=530.2,569.3
XS Rating Curve= 0 ,0
Exp/Cntr=0.3,0.1

Type RM Length L Ch R = 1 ,11039.7 ,676.3,673.3,670.8
XS GIS Cut Line= 4
     1920916.529      574033.174     1921016.053      574164.294
     1921325.685      574753.542     1921469.442      574908.358
#Sta/Elev= 30
       0  826.51     9.7  825.11    58.1  821.47    87.2  817.96   106.5  814.46
   125.9  809.51   135.6  806.58   203.8  781.72   262.5  759.21   301.7  745.62
   311.4  742.52   321.2  740.26     331  739.17   399.6  735.84     517  732.07
   575.8  729.21   595.3  728.38   611.1  729.09   644.3  733.62   654.1  736.32
   663.8   741.2   673.6  746.88   683.4  750.85     703  753.51   722.6   763.3
   732.4  767.27   859.1  802.39   887.9  809.15  1022.3  836.98  1041.5  841.42
#Mann= 3 , 0 , 0
       0     .08       0   575.8    .045       0   611.1      .1       0
Bank Sta=575.8,611.1
XS Rating Curve= 0 ,0
Exp/Cntr=0.3,0.1

Type RM Length L Ch R = 1 ,10366.4 ,566,561.7,557.3
XS GIS Cut Line= 4
     1920387.311      574355.444     1920488.415      574595.567
      1920777.51      575047.376     1920903.891      575116.886
#Sta/Elev= 30
       0  847.87    38.6  847.87    67.6  849.55   106.2   849.7   115.8  849.04
   125.4  847.12     193  822.16   260.5  796.03     319  770.74   377.6     744
   387.3  740.57   445.8  734.21   465.3   729.8   475.1  728.29   484.8  728.09
   494.6  729.18   504.4  731.28   514.1  733.25   523.9  733.98   601.9  734.83
   611.6  735.56   621.4  737.79   699.4   772.7   709.2  775.29   718.9  776.31
   728.7  778.59   748.2  791.93   757.9   796.2   796.9  809.18   941.2   850.3
#Mann= 3 , 0 , 0
       0     .08       0   465.3    .045       0   504.4     .08       0
Bank Sta=465.3,504.4
XS Rating Curve= 0 ,0
Exp/Cntr=0.3,0.1

Type RM Length L Ch R = 1 ,9804.7  ,431.7,428.8,426
XS GIS Cut Line= 4
     1919899.167      574756.702     1920114.014      575037.898
     1920357.296      575289.079     1920553.185      575371.226
#Sta/Elev= 30
       0  793.74    19.7  809.83    39.3  822.68    78.6  842.84    98.3  850.48
   108.1  851.74   206.4  852.76   216.3  851.48   226.1  847.44   265.4  825.17
   334.2  790.98     383  768.29   441.3  743.29   460.7   738.8   548.2  729.51
   567.6  727.03  579.45  728.66     587  733.98   606.4  751.66   616.1   758.1
   635.6  767.12     655  773.48   693.8  782.45   713.2  783.43   722.9  786.22
   742.2   794.8   751.8  796.88   790.5  798.38   829.1   803.5     916  824.37
#Mann= 3 , 0 , 0
       0     .08       0   548.2    .045       0  579.45     .08       0
Bank Sta=548.2,579.45
XS Rating Curve= 0 ,0
Exp/Cntr=0.3,0.1

Type RM Length L Ch R = 1 ,9375.8  ,310.5,310.6,310.7
XS GIS Cut Line= 4
     1919762.176      575291.791       1919861.7      575410.273
      1920056.01      575565.089     1920321.408      575587.205
#Sta/Elev= 30
       0  835.73      29  820.08    48.4  810.19    67.7  800.85    96.7  787.49
   145.1  766.72   183.4  749.49     193   745.6   212.1  738.51   240.7  729.27
   250.3     727   259.8  727.84   263.9  729.68   269.4  732.14     279  738.14
   288.5  743.59   345.8  772.39   355.4  775.72     365  777.82   403.2  784.78
   469.8  794.54   507.8  797.89   517.3  797.84   536.3  795.81   545.8  795.29
   631.4  795.75     641  795.99   650.5  796.76     660  798.44   669.5  800.96
#Mann= 3 , 0 , 0
       0     .08       0   240.7    .045       0   263.9     .08       0
Bank Sta=240.7,263.9
XS Rating Curve= 0 ,0
Exp/Cntr=0.3,0.1