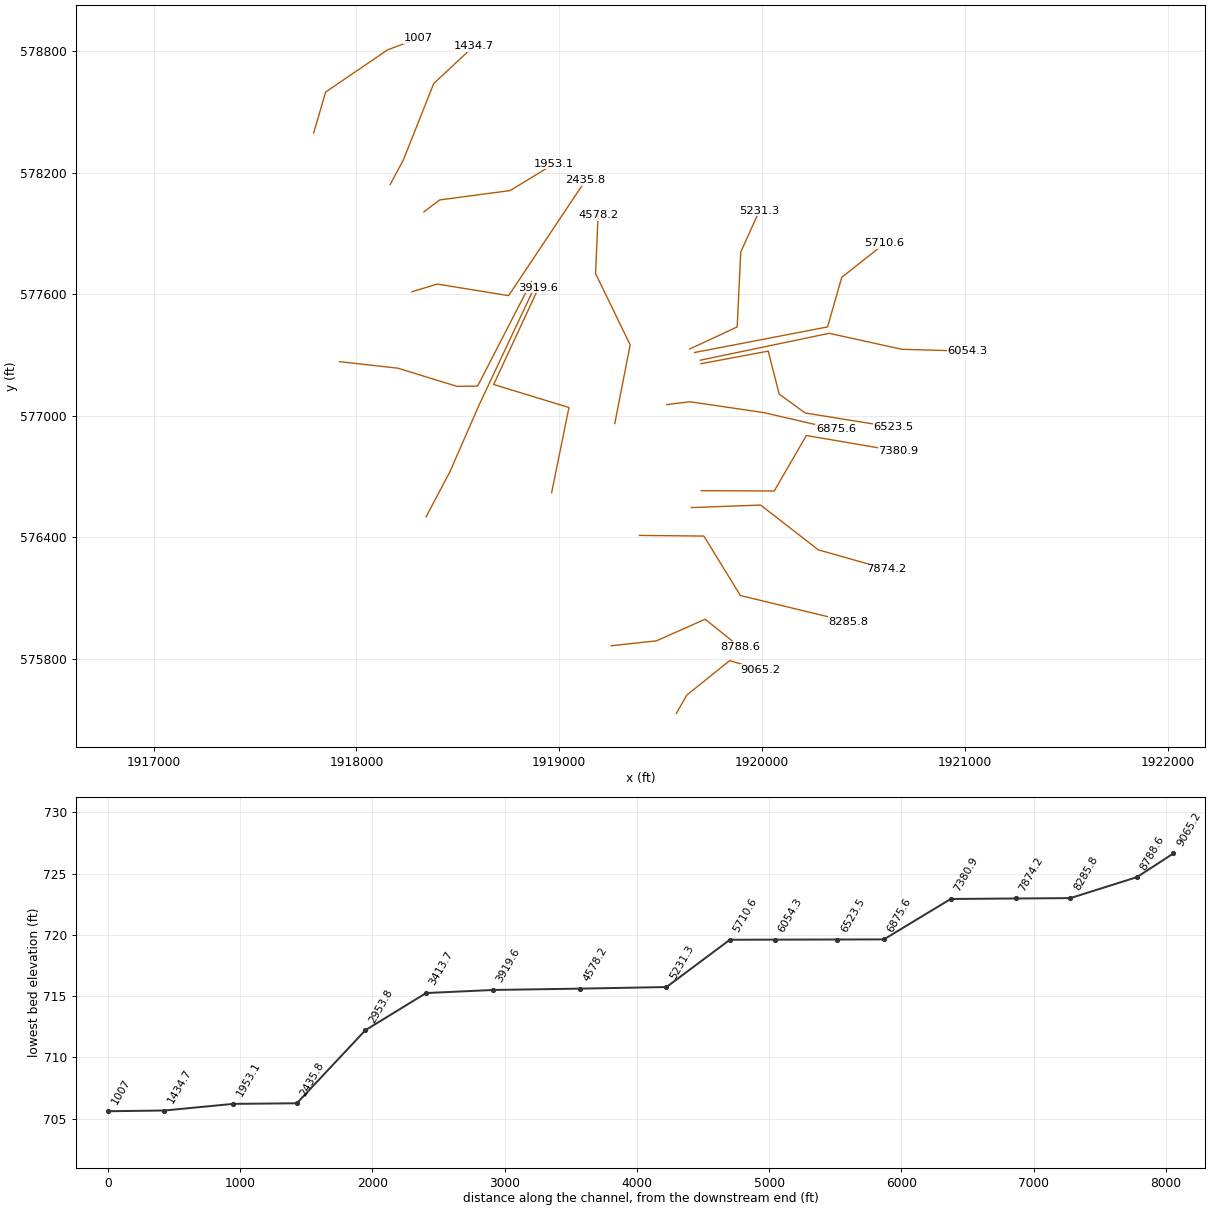
HEC-RAS study RFBgSndyCk.prj: RFBgSndyCk

--- RFBgSndyCk.g01 (geometry) --- (continued)

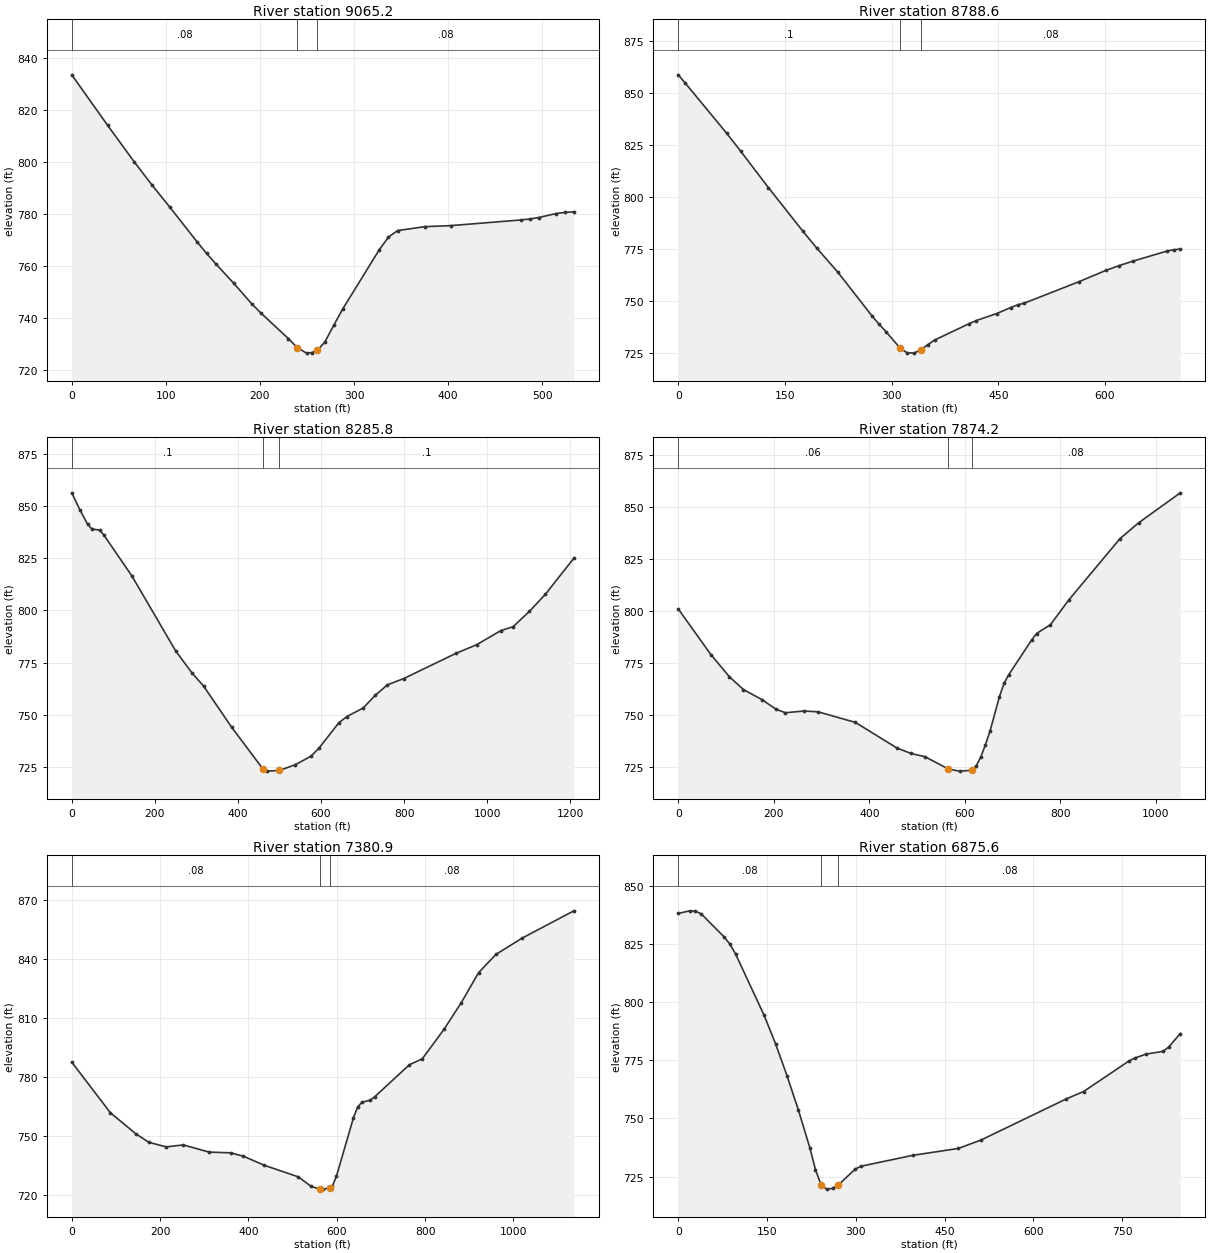
Type RM Length L Ch R = 1 ,9065.2  ,282.7,276.6,270.4
XS GIS Cut Line= 4
     1919577.021      575529.989     1919629.123      575620.601
     1919839.797      575790.499     1919991.573      575745.193
#Sta/Elev= 30
       0  833.58      38  814.23    66.5  800.08    85.5  791.13   104.5  782.61
   133.5  769.25   143.2  764.99   152.8  761.06   172.2  753.46   191.5  745.51
   201.2  741.99   230.2  732.23   239.8  728.73   249.5  726.65     255  726.85
  260.99  727.72   268.8  730.81   278.5  737.42   288.2  743.76   326.8  766.37
   336.5  771.18   346.2  773.73   375.2  775.24   403.1  775.65   477.7  777.83
     487  778.19   496.3  778.76   514.9  780.29   524.2  780.72   533.6  780.94
#Mann= 3 , 0 , 0
       0     .08       0   239.8    .045       0  260.99     .08       0
Bank Sta=239.8,260.99
XS Rating Curve= 0 ,0
Exp/Cntr=0.3,0.1

Type RM Length L Ch R = 1 ,8788.6  ,535.4,502.8,470.1
XS GIS Cut Line= 4
     1919256.207      575864.109     1919479.169      575888.369
     1919719.075      575995.229     1919889.689       575857.79
#Sta/Elev= 30
       0  858.77     9.8  854.83    68.3  830.54    87.8     822   126.8  804.45
   175.5  783.33     195  775.24   224.3  763.76   272.9  742.44   282.6  738.59
   292.4  734.95   311.8   727.2   321.6  724.93   331.3  724.71     341  726.27
   350.7  728.74   360.5  731.01   409.1  738.92   418.8  740.37     448  743.78
   467.4  746.67   477.2  747.96   486.9  748.83   563.1  759.06   601.2  764.54
   620.3  766.91   639.3     769   686.9  773.85   696.5   774.5     706  774.84
#Mann= 3 , 0 , 0
       0      .1       0   311.8    .045       0     341     .08       0
Bank Sta=311.8,341
XS Rating Curve= 0 ,0
Exp/Cntr=0.3,0.1

Type RM Length L Ch R = 1 ,8285.8  ,402.4,411.6,420.8
XS GIS Cut Line= 4
     1919395.226      576409.124     1919712.756      576405.965
     1919892.848      576112.131     1920423.778      575983.366
#Sta/Elev= 30
       0  856.23    19.2  848.22    38.5  841.09    48.1  838.95    67.4  838.35
      77  836.11   144.3  816.56   250.2  780.52   288.7  770.18   317.6  763.64
   384.6  744.08   461.1  723.78   470.7     723   499.4  723.31   537.7  726.03
     576  730.17   595.2  734.04     643  746.19   662.2  749.13   701.2  753.19
   730.5  759.32   759.7   764.3   798.8   767.3   925.6  779.46   974.4   783.5
  1032.9  790.29  1062.2  792.12  1101.2  799.42  1140.2   807.7  1208.5  824.94
#Mann= 3 , 0 , 0
       0      .1       0   461.1    .045       0   499.4      .1       0
Bank Sta=461.1,499.4
XS Rating Curve= 0 ,0
Exp/Cntr=0.3,0.1

Type RM Length L Ch R = 1 ,7874.2  ,455.4,493,530.7
XS GIS Cut Line= 4
     1919651.146      576546.563     1919992.373      576559.201
     1920276.728      576338.035     1920612.891      576242.515
#Sta/Elev= 30
       0  800.98    68.3  779.02   107.3   768.3   136.6  762.19   175.6  757.31
   204.9  752.72   224.4  751.05   263.4  751.87   292.7  751.49   370.7  746.43
   458.3  734.03   487.5  731.46   516.7   729.9   565.4     724     589  722.97
   614.1  723.36   623.8  725.45   633.6  729.85   643.3  735.73     653  742.39
   672.5   758.8   682.2   765.2     692  769.36   740.5  786.24   750.2  789.15
   779.4  793.42   818.2  805.43     925   834.8   963.8  842.36  1051.2   856.8
#Mann= 3 , 0 , 0
       0     .06       0   565.4    .045       0   614.1     .08       0
Bank Sta=565.4,614.1
XS Rating Curve= 0 ,0
Exp/Cntr=0.3,0.1

Type RM Length L Ch R = 1 ,7380.9  ,532.2,505.3,478.3
XS GIS Cut Line= 4
     1919700.118       576630.29     1920059.532      576628.663
     1920218.103      576902.765      1920672.11      576824.859
#Sta/Elev= 30
       0  787.46    87.4  761.74   145.7  750.93   174.8   746.7   213.7  744.39
   252.6   745.4   310.8  741.75   359.4  741.38   388.2  739.69   436.2  735.02
     513  729.16   541.7  724.34   560.9  722.95   569.9  722.93   584.9  723.67
   589.7  724.32   599.3  729.54   637.7  759.18   647.3  764.69   656.9  767.07
   676.1  768.16   685.9  769.88   764.3  786.12   793.7  789.18   842.7  804.12
   881.9  817.69   921.1  832.96   960.3   842.2  1019.1  850.42  1136.7  864.35
#Mann= 3 , 0 , 0
       0     .08       0   560.9    .045       0   584.9     .08       0
Bank Sta=560.9,584.9
XS Rating Curve= 0 ,0
Exp/Cntr=0.3,0.1

Type RM Length L Ch R = 1 ,6875.6  ,378.8,352.1,325.4
XS GIS Cut Line= 4
     1919529.505      577055.244     1919644.827      577069.461
      1920007.43       577016.03     1920363.615      576933.603
#Sta/Elev= 30
       0  838.05    19.4  839.18      29  839.06    38.7  837.89    77.5  827.97
    87.2   824.9    96.8  820.69   145.1  794.29   164.4   782.1   183.7   768.4
     203  753.63   222.3  737.44   231.9  728.01   241.6  721.25   251.2  719.63
   260.9  719.96   270.5  721.43   299.4  728.33   309.1  729.48   395.9  734.13
   473.1   737.1   511.6  740.72   655.9  758.42   684.8  761.55   761.7   774.7
   771.3  775.93   790.6  777.64   819.4  778.83   829.1  780.78   848.3  786.48
#Mann= 3 , 0 , 0
       0     .08       0   241.6    .045       0   270.5     .08       0
Bank Sta=241.6,270.5
XS Rating Curve= 0 ,0
Exp/Cntr=0.3,0.1

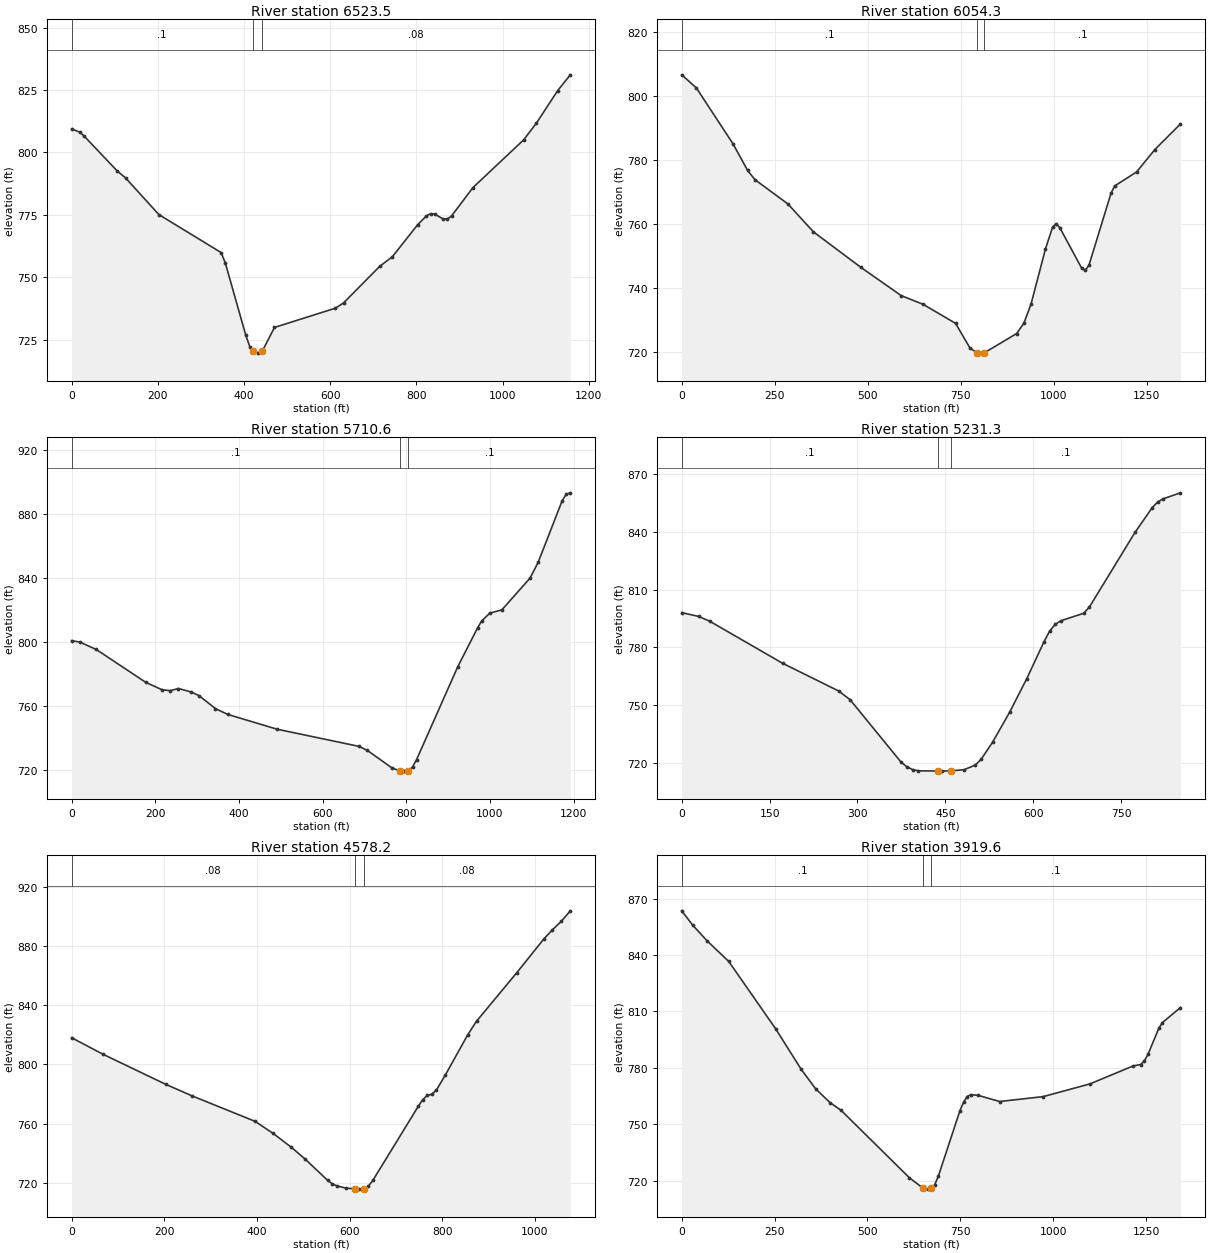
Type RM Length L Ch R = 1 ,6523.5  ,440.8,469,496.9
XS GIS Cut Line= 5
     1919698.538      577257.452     1920030.083      577319.582
     1920083.998      577107.375     1920211.958       577014.17
     1920648.512      576943.541
#Sta/Elev= 30
       0   809.4    19.3  808.08    28.9  806.57     106  792.54   125.3  789.76
   202.4  775.11   346.8   759.9   356.4  755.82     404  726.78   413.5  722.13
   420.4  720.52   432.5  719.62     442  720.31   470.6  729.91   612.1  737.63
   630.8  739.73   714.6  754.36     744  758.24     803   771.1   822.7  774.53
   832.5  775.46   842.3  775.28     862  773.34   871.8  773.36   881.6  774.61
   930.8  785.89  1048.7  805.06  1078.2  811.74  1127.3  824.71  1156.8  831.07
#Mann= 3 , 0 , 0
       0      .1       0   420.4    .045       0     442     .08       0
Bank Sta=420.4,442
XS Rating Curve= 0 ,0
Exp/Cntr=0.3,0.1

Type RM Length L Ch R = 1 ,6054.3  ,311.9,343.5,375.6
XS GIS Cut Line= 4
     1919695.379      577274.829      1920330.44      577407.529
     1920689.044      577328.541     1921013.226      577319.582
#Sta/Elev= 30
       0  806.62    39.3  802.51   137.6  785.07   176.9  776.74   196.6  773.85
   285.1  766.27   353.9  757.52   481.7   746.4   589.8  737.59   648.8  734.86
   735.8  728.92   774.4  721.24   793.7  719.66   803.4  719.61     813   719.7
     900  725.74   919.4  728.94   938.7  734.95   977.3  752.13   996.6     759
  1006.3  760.07    1016  758.83  1074.9  746.14  1084.8  745.49  1094.6  747.18
  1153.6  769.59  1163.4  771.88  1222.4  776.26  1271.5  783.26  1340.3  791.27
#Mann= 3 , 0 , 0
       0      .1       0   793.7    .045       0     813      .1       0
Bank Sta=793.7,813
XS Rating Curve= 0 ,0
Exp/Cntr=0.3,0.1

Type RM Length L Ch R = 1 ,5710.6  ,474,479.2,484.4
XS GIS Cut Line= 4
     1919666.943      577312.743     1920322.541      577439.124
     1920392.532      577684.296     1920603.737       577851.44
#Sta/Elev= 30
       0  800.92    19.6  799.99    58.9  795.41   176.7  775.01     216  770.31
   235.6  769.73   255.3  771.08   284.7  769.01   304.4  766.68   343.6  758.59
   373.1  754.94   490.9  745.74   687.3     735   706.9   732.5   765.7   721.6
   785.7  719.67   795.2   719.6     805  719.95   814.8  722.17   824.6  726.81
   922.6  784.45   970.7  809.07   980.4  813.24   999.6  818.07  1028.4   820.1
  1095.8  839.89    1115  849.64  1172.7  888.21  1182.4  892.21    1192  893.01
#Mann= 3 , 0 , 0
       0      .1       0   785.7    .045       0     805      .1       0
Bank Sta=785.7,805
XS Rating Curve= 0 ,0
Exp/Cntr=0.3,0.1

Type RM Length L Ch R = 1 ,5231.3  ,641.9,653.1,664.3
XS GIS Cut Line= 4
     1919643.247      577330.121     1919877.051      577439.124
     1919894.428      577808.786     1919986.054      578012.574
#Sta/Elev= 30
       0     798    28.7  796.04    47.8  793.53     172  771.74   267.7  757.36
   287.2  752.88   374.8  720.28   384.6  717.95   394.3  716.51     404  715.91
  437.02   715.8  444.08  715.74   458.9   715.9     482  716.45   501.4  718.95
   511.2   721.9   530.6  730.72   559.9  746.36   589.1  763.76   618.3  782.77
     628  788.38   637.8  791.97   647.5  793.82   686.3  797.66     696  800.92
   773.8  839.61   802.9  852.36   812.6  855.45   822.3  857.12   851.5  860.18
#Mann= 3 , 0 , 0
       0      .1       0  437.02    .045       0   458.9      .1       0
Bank Sta=437.02,458.9
XS Rating Curve= 0 ,0
Exp/Cntr=0.3,0.1

Type RM Length L Ch R = 1 ,4578.2  ,639.8,658.4,677
XS GIS Cut Line= 4
     1919273.585      576962.038     1919349.413      577350.658
     1919178.799      577702.943     1919191.437      577992.038
#Sta/Elev= 30
       0  818.02    67.6  806.87   202.8  786.56   260.8  778.59     396  761.48
   435.1  753.29   474.2  743.96   503.6  736.09   552.5  721.64   562.3  719.29
   572.1  717.86   591.7  716.32   611.2   715.8  621.32  715.61   631.3  715.98
   640.6  717.56   650.4  721.54   748.2   771.5     758  776.13   767.8  778.97
   777.6  779.81   787.4  782.54   806.7  792.68   854.9  819.81   874.2   829.2
     961  861.95  1018.9   884.6  1038.2  891.08  1057.4  896.79  1076.7  903.85
#Mann= 3 , 0 , 0
       0     .08       0   611.2    .045       0   631.3     .08       0
Bank Sta=611.2,631.3
XS Rating Curve= 0 ,0
Exp/Cntr=0.3,0.1

Type RM Length L Ch R = 1 ,3919.6  ,544.4,505.9,467.3
XS GIS Cut Line= 4
     1918962.373      576620.811      1919047.68      577041.026
     1918676.438      577154.768     1918897.603      577631.854
#Sta/Elev= 30
       0  863.48    29.2  855.92    68.2  847.53   126.7  836.54   253.4  800.59
   321.6  779.19   360.6  768.83   399.6  761.44   428.8  757.44   613.2   721.5
     649  716.11  661.98   715.5   671.5  715.85   681.2  717.85   690.9  722.38
   749.1  757.27   758.8  761.72   768.5  764.73   778.2  765.74   797.6  765.38
     856  762.09   972.9  764.68  1099.5  771.47  1216.3  781.08  1235.8  781.74
  1245.5  783.66  1255.3   787.1  1284.5     801  1294.2  804.05  1342.9  812.06
#Mann= 3 , 0 , 0
       0      .1       0     649    .045       0   671.5      .1       0
Bank Sta=649,671.5
XS Rating Curve= 0 ,0
Exp/Cntr=0.3,0.1

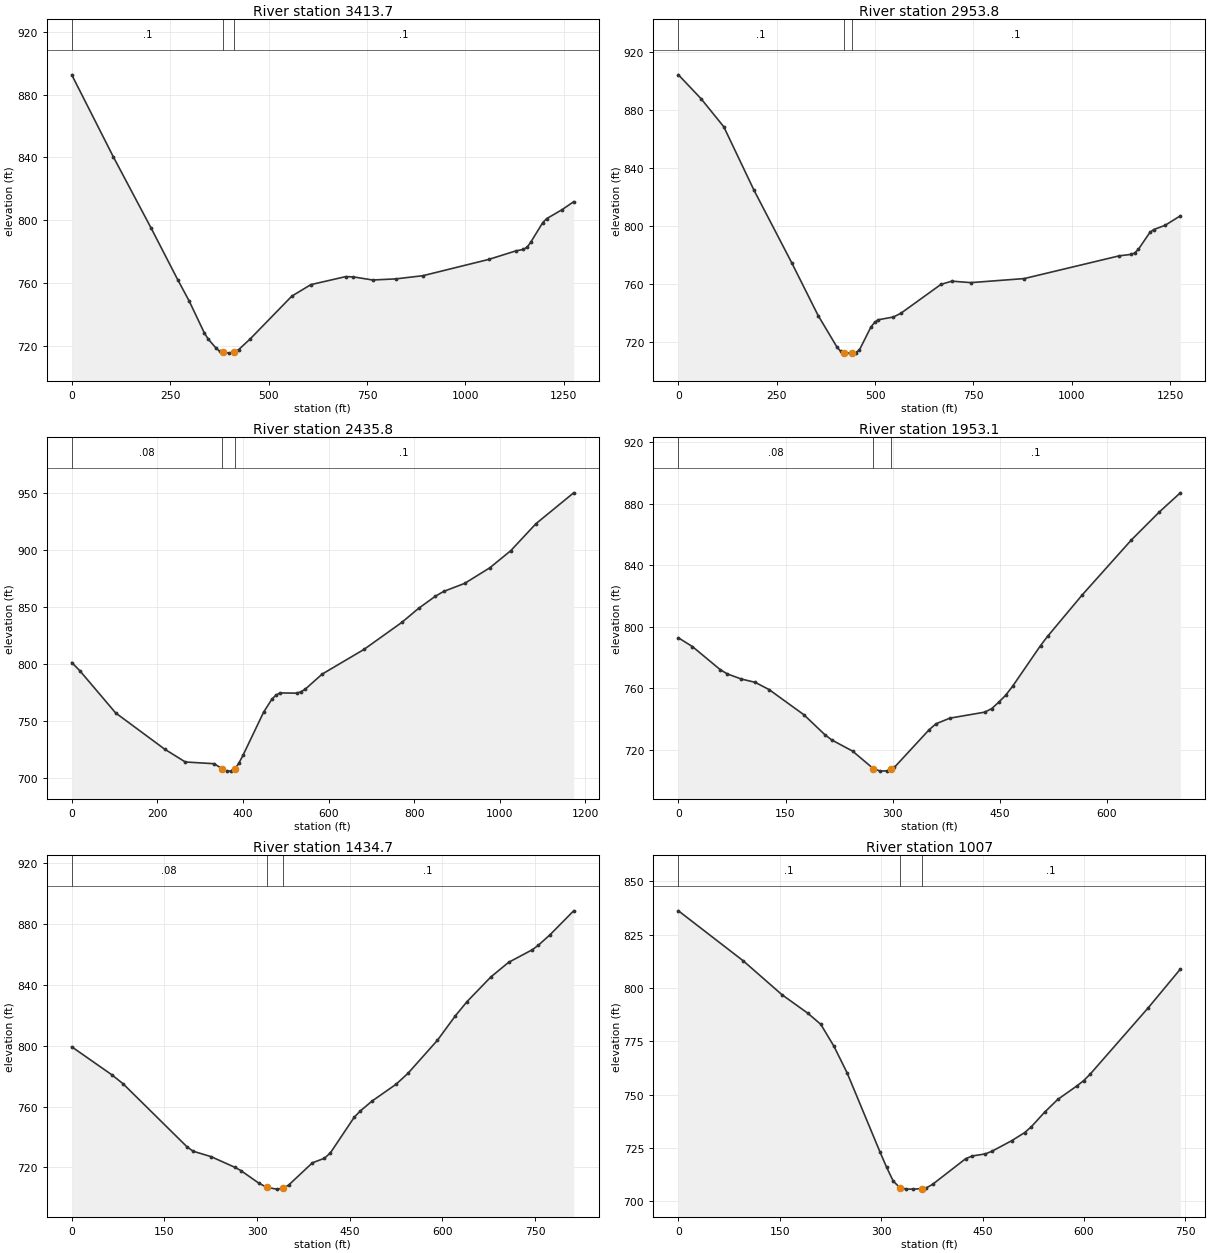
Type RM Length L Ch R = 1 ,3413.7  ,492.7,459.6,426.4
XS GIS Cut Line= 4
     1918343.339      576501.038     1918460.011      576721.916
     1918606.928      577058.403     1918886.545       577653.97
#Sta/Elev= 30
       0   892.7   105.7  840.37   201.8  794.88   269.1   762.1   298.1  748.56
   336.8  728.13   346.4  724.29   365.7  718.68   375.4  716.46   385.1  715.86
  399.44  715.25   411.3  716.01   423.7  717.43   452.7  724.17     559  751.59
   607.3  758.92   695.5  764.02   715.2  763.87   764.3  761.88   823.2  762.59
   891.9  764.62  1058.9  774.98  1127.6   780.4  1147.2  781.41  1157.1  782.87
  1166.9  786.39  1196.3  798.43  1206.2  800.98  1245.4  806.71  1274.9  811.79
#Mann= 3 , 0 , 0
       0      .1       0   385.1    .045       0   411.3      .1       0
Bank Sta=385.1,411.3
XS Rating Curve= 0 ,0
Exp/Cntr=0.3,0.1

Type RM Length L Ch R = 1 ,2953.8  ,514.6,517.9,521.1
XS GIS Cut Line= 5
     1917917.634      577267.463     1918204.091      577235.336
     1918496.346       577145.29      1918597.45      577146.869
     1918862.848      577663.449
#Sta/Elev= 30
       0  904.38    57.6  887.88   115.3  868.52   192.2  824.67   288.2  774.51
   355.2  738.18   402.9  716.48   412.5  713.44   420.2  712.52  426.07  712.21
   441.2   712.3   450.7  712.56   460.3  714.48   488.9  729.98   498.5  733.39
   508.1  735.25   546.3  737.14   565.4   739.7   667.6   759.7   695.2   761.9
   743.6   760.9   879.1  763.69  1121.1  779.42  1150.1  780.37  1159.8  781.33
  1169.5  783.94  1198.5  795.52  1208.2  797.52  1237.2  800.45    1276  807.02
#Mann= 3 , 0 , 0
       0      .1       0   420.2    .045       0   441.2      .1       0
Bank Sta=420.2,441.2
XS Rating Curve= 0 ,0
Exp/Cntr=0.3,0.1

Type RM Length L Ch R = 1 ,2435.8  ,475.7,482.2,488.8
XS GIS Cut Line= 4
       1918273.6      577612.897     1918398.401      577650.811
     1918750.184      577593.684     1919129.994      578164.603
#Sta/Elev= 30
       0  801.31    18.6  794.23   102.5   757.2   217.1  725.47   265.3  714.25
   332.7  712.75   351.6  708.25   361.6  706.27   371.2  706.25   380.9  708.04
   390.5  713.32   400.1  720.18   448.3  757.92   467.6  769.28   477.2   772.8
   486.8  774.71     526  774.49   535.8  775.77   545.6  778.02   584.8  791.13
   682.7  812.78   770.9  836.37   810.1  848.67   849.3   859.3   868.9  863.54
   917.8  870.56   976.6   884.2  1025.6  899.21  1084.4  922.81  1172.5  949.83
#Mann= 3 , 0 , 0
       0     .08       0   351.6    .045       0   380.9      .1       0
Bank Sta=351.6,380.9
XS Rating Curve= 0 ,0
Exp/Cntr=0.3,0.1

Type RM Length L Ch R = 1 ,1953.1  ,494.6,518.5,542.5
XS GIS Cut Line= 4
     1918332.578      578007.572     1918410.512      578066.549
     1918758.058      578112.889     1918975.011      578245.588
#Sta/Elev= 30
       0  792.86    19.6  787.18    58.6  772.14    68.4  769.43      88  766.09
   107.5  763.92     127  759.19   175.6  742.88   204.9  729.95   214.6  726.49
   243.8  719.23     273  707.79   282.8   706.2   292.5   706.4   297.1  707.45
   302.3  708.63     351  733.11   360.7     737   380.2  740.66   428.9  744.55
   438.6  746.84   448.4  750.98   458.1   755.5   467.9  761.38     507  787.84
   516.8  793.81   565.7  820.95   634.2  856.51   673.3  874.68   702.7  887.13
#Mann= 3 , 0 , 0
       0     .08       0     273    .045       0   297.1      .1       0
Bank Sta=273,297.1
XS Rating Curve= 0 ,0
Exp/Cntr=0.3,0.1

Type RM Length L Ch R = 1 ,1434.7  ,441.1,427.8,414.4
XS GIS Cut Line= 4
     1918166.177      578142.378     1918231.474      578264.545
     1918381.024       578641.58     1918576.913      578824.831
#Sta/Elev= 30
       0  799.26    64.6  780.93    83.1  774.95   186.8   733.4   196.5  730.59
   225.4  727.04   264.1     720   273.7  717.88   302.7  709.62   315.8  706.81
   331.7  705.66   341.3  706.12     351   708.3   389.6     723   408.9  725.94
   418.6  729.49   457.2  752.92   466.9  757.01   486.2  763.62   524.8  774.59
   544.1  781.77     592  803.62   620.8  819.58   639.9  829.03   678.2  845.14
     707  854.79   745.3  863.07   754.9  865.95   774.1  872.94   812.4   888.7
#Mann= 3 , 0 , 0
       0     .08       0   315.8    .045       0   341.3      .1       0
Bank Sta=315.8,341.3
XS Rating Curve= 0 ,0
Exp/Cntr=0.3,0.1

Type RM Length L Ch R = 1 ,1007    ,424.2,423.4,422.5
XS GIS Cut Line= 4
     1917789.142      578397.245      1917848.12      578599.453
     1918153.539      578807.981     1918305.195      578864.852
#Sta/Elev= 30
       0  836.22    95.7   812.8   153.2  796.84   191.5  788.14   210.6  782.95
   230.1  772.62   249.6  760.12   298.2  723.01     308  715.82   317.7  709.39
   327.4  706.33   337.2  705.64   346.9   705.6   359.7  705.82   366.4  706.13
   376.1  707.88   424.7  719.84   434.5  721.15   453.9  722.13   463.7  723.37
   492.9  728.32   512.3  732.16   522.1  734.91   541.5  741.66     561  747.68
     590  754.18   599.5  756.54     609  759.55   694.8  790.66   742.4  808.86
#Mann= 3 , 0 , 0
       0      .1       0   327.4    .045       0   359.7      .1       0
Bank Sta=327.4,359.7
XS Rating Curve= 0 ,0
Exp/Cntr=0.3,0.1