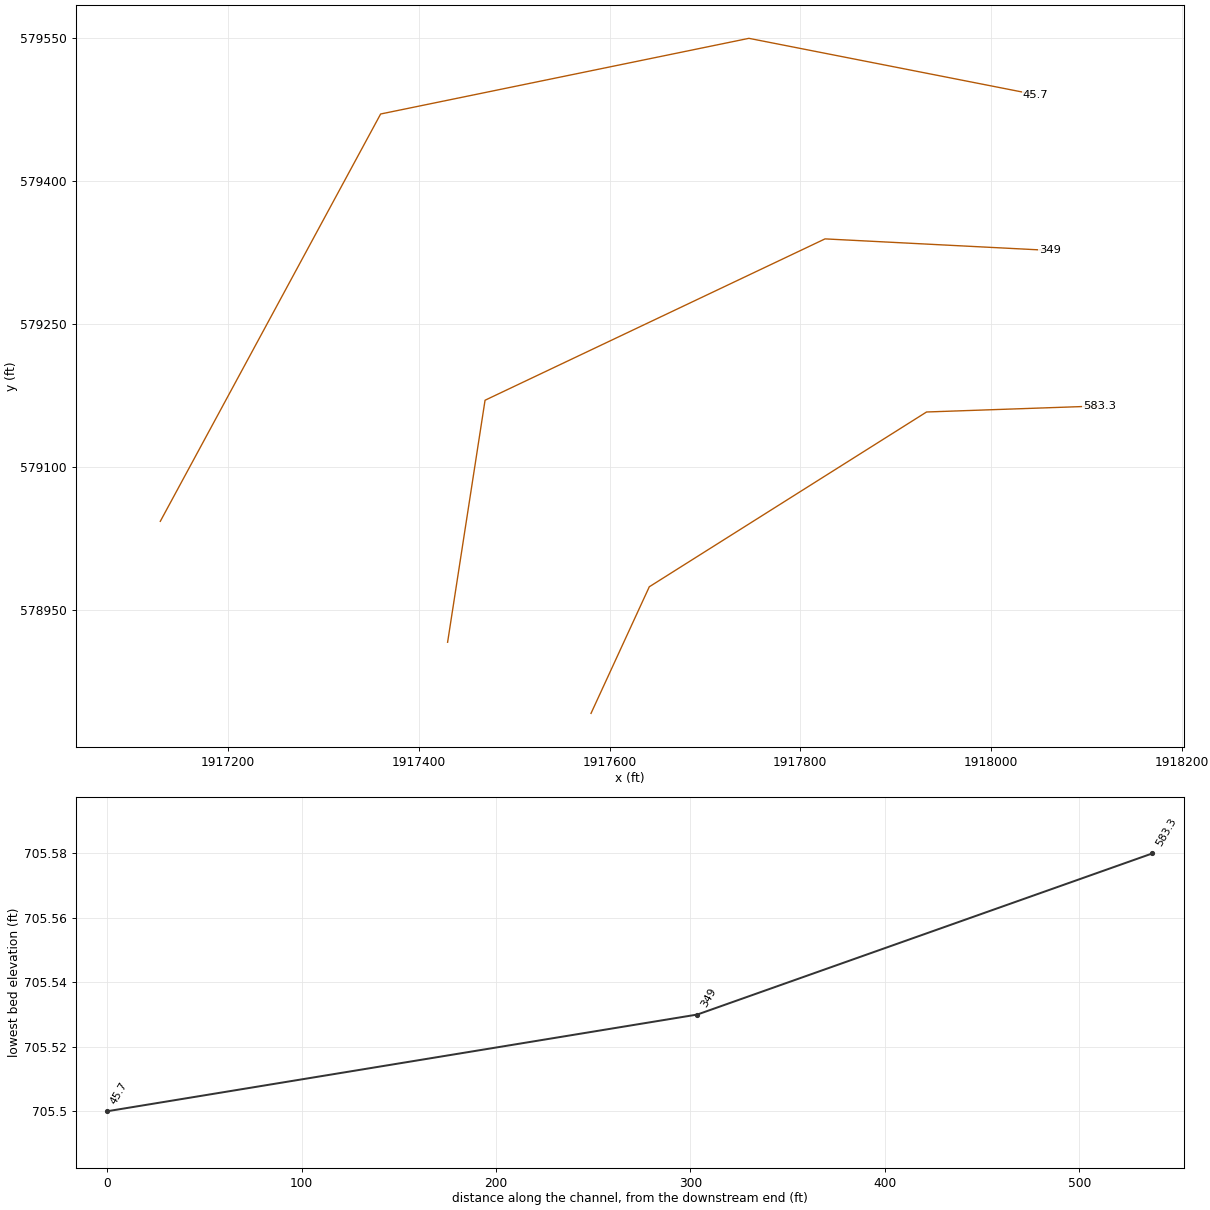
HEC-RAS study RFBgSndyCk.prj: RFBgSndyCk

--- RFBgSndyCk.g01 (geometry) --- (continued)

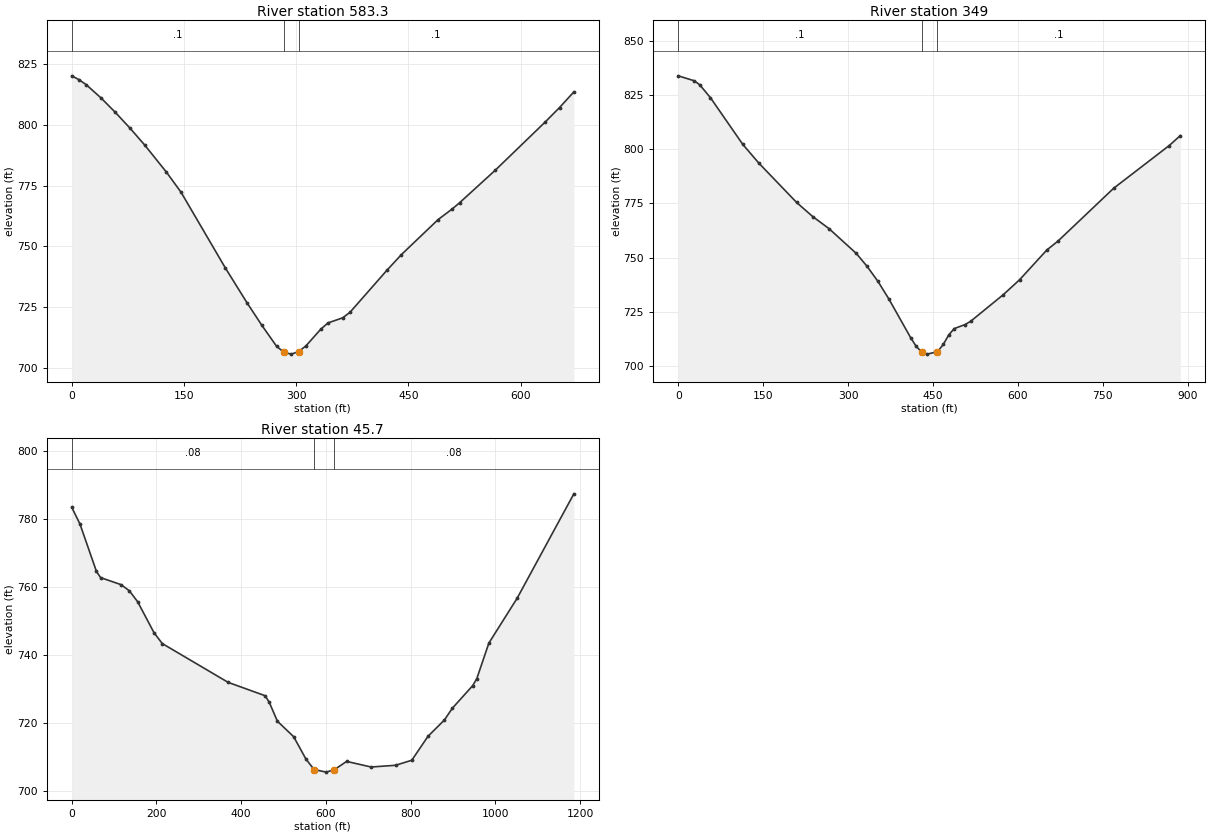
Type RM Length L Ch R = 1 ,583.3   ,236.8,234.1,231.4
XS GIS Cut Line= 4
     1917580.615      578841.682     1917641.699      578974.381
     1917932.373      579157.633     1918113.519      579163.952
#Sta/Elev= 30
       0  820.25     9.7  818.66    19.5  816.55      39  811.17    58.4  805.14
    77.9  798.66    97.4  791.76   126.6  780.53   146.1  772.25     205  741.22
   234.4  726.64   254.1  717.42   273.7  708.82   283.5  706.35   293.4  705.58
   303.1  706.62     313  708.99   332.6   715.8   342.4  718.44   362.1  720.54
   371.9  722.84     421  740.07   440.6  746.61   489.7  761.04   508.8  765.48
   518.3  767.95     566  781.36   632.8  801.25   651.9  807.19     671  813.62
#Mann= 3 , 0 , 0
       0      .1       0   283.5    .045       0   303.1      .1       0
Bank Sta=283.5,303.1
XS Rating Curve= 0 ,0
Exp/Cntr=0.3,0.1

Type RM Length L Ch R = 1 ,349     ,310.2,303.5,295.8
XS GIS Cut Line= 4
     1917430.265      578916.246      1917469.53       579169.96
     1917825.939      579339.103     1918061.531      579327.022
#Sta/Elev= 30
       0  833.77    28.5  831.47      38  829.63      57  823.66   114.1  802.16
   142.6   793.5   209.2  775.41   237.7   768.9   266.4  763.36   314.5  751.96
   333.7  745.97     353     739   372.2  730.92   410.7  713.09   420.3  709.16
   429.9  706.56   439.6  705.53     458  706.62   468.4  710.04     478   714.4
   487.7   717.3   506.9  719.16   516.5  720.63   574.3  732.92   603.1  739.79
   651.2   753.5   670.9   757.6   769.2  781.93   867.5  801.65   887.1  806.22
#Mann= 3 , 0 , 0
       0      .1       0   429.9    .045       0     458      .1       0
Bank Sta=429.9,458
XS Rating Curve= 0 ,0
Exp/Cntr=0.3,0.1

Type RM Length L Ch R = 1 ,45.7    ,32,45.7,60.4
XS GIS Cut Line= 4
     1917129.078      579043.014     1917360.058      579470.023
     1917746.152      579549.344     1918046.116      579490.434
#Sta/Elev= 30
       0   783.5    19.4  778.57    58.3  764.61      68   762.8   116.5  760.72
   135.9  758.92   155.4  755.72   194.2  746.56   213.6  743.38     369  731.95
   456.4  728.01   466.1  726.11   485.5  720.49   523.9  715.93   552.8  709.35
     572  706.27   600.8   705.5   620.1  706.24   648.9  708.66   706.6  707.01
   764.3  707.51   802.7     709   841.2  716.09   879.6  720.84   898.7  724.36
   946.5  730.98   956.1     733   984.7  743.52  1051.6  756.76  1185.3  787.48
#Mann= 3 , 0 , 0
       0     .08       0     572    .045       0   620.1     .08       0
#XS Ineff= 2 , 0
       0                     745       0
Permanent Ineff=
       F       F
Bank Sta=572,620.1
XS Rating Curve= 0 ,0
Exp/Cntr=0.3,0.1

Chan Stop Cuts=-1
Use User Specified Reach Order=0
Composite Channel Slope=5